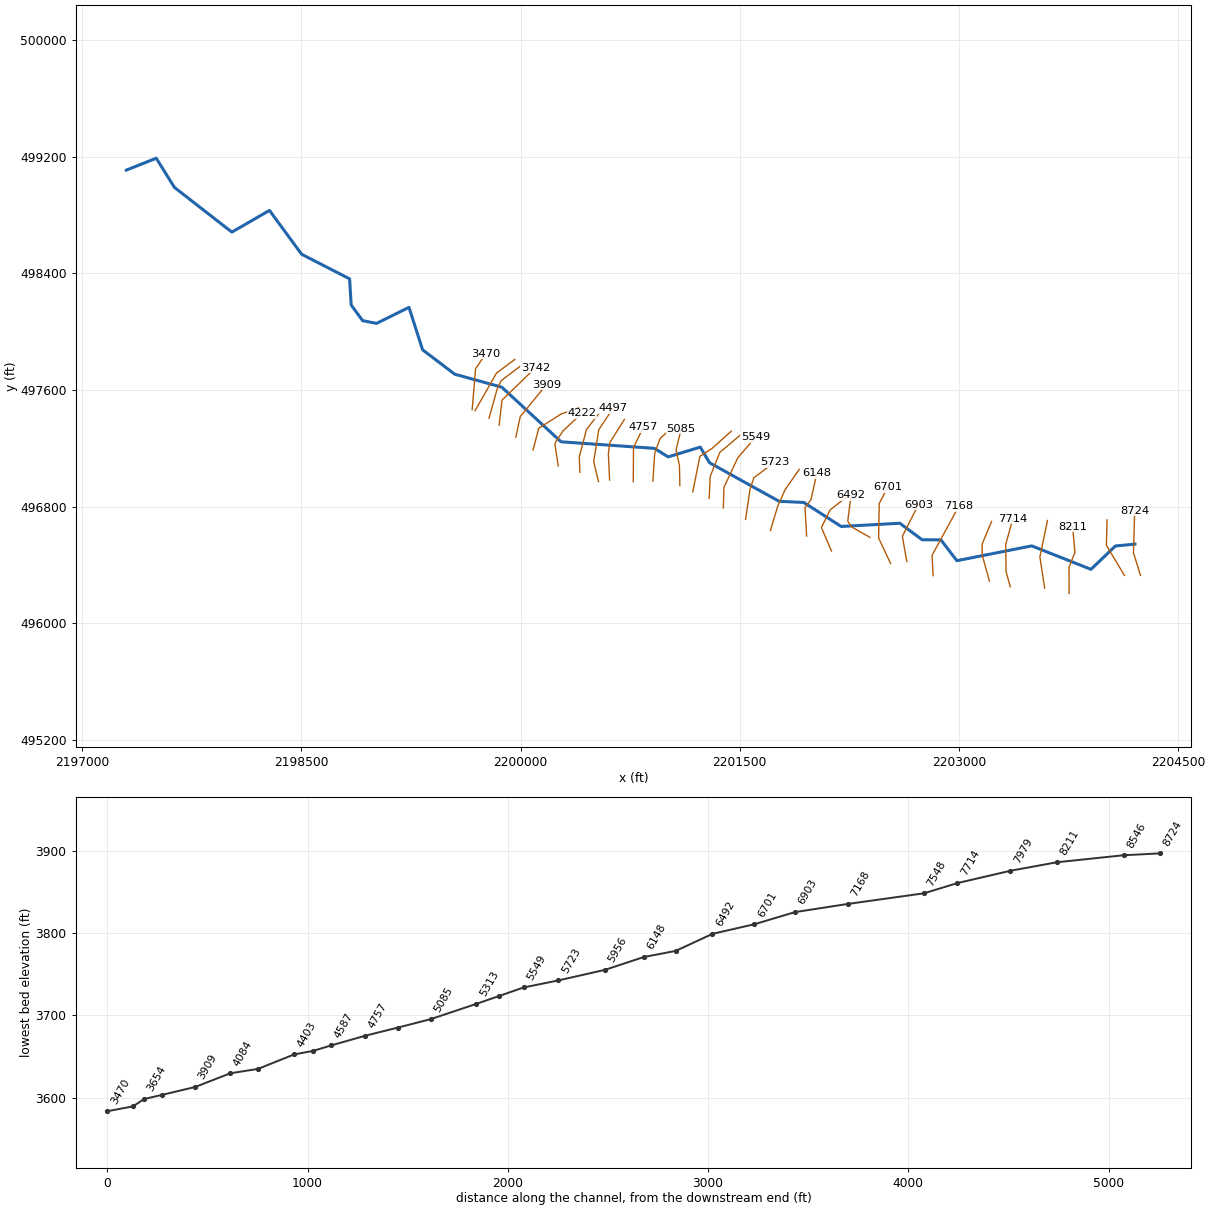
--- RFKTEACK.prj (project) ---

Proj Title=RFKTEACK
Current Plan=p01
Default Exp/Contr=0,0
English Units
Geom File=g01
Flow File=f01
Plan File=p01
Background Map Layer=Inundation Boundary (01pct Value_0)
Background Map Layer=Inundation Boundary (01pct Value_0)
Background Map Layer=Inundation Boundary (01pct Value_0)
Background Map Layer=QC1
BEGIN DESCRIPTION:
----------MODEL BY WOOD PLC 2021----------
Stream Name: Right Fork Tea Creek
Flood Zone: Approximate
Pocahontas County, WV
HEC-RAS Version: RAS 6.1
Vertical Datum: NAVD88
Projection: NAD 1983 StatePlane West Virginia S FIPS 4702 (US Feet)
Terrain: 1-meter LIDAR (FEMA Region III 3DEP collected 2016-2018)
Land Use: 2019 NLCD
Hydrologic Method:
WV SIR2010-5033 regression equations
END DESCRIPTION:
DSS Export Rating Curves= 0
DSS Export Rating Curve Sorted= 0
DSS Export Volume Flow Curves= 0
DXF OffsetX= 0
DXF OffsetY= 0
DXF ScaleX= 0
DXF ScaleY= 0

--- RFKTEACK.p01 (plan) ---

Plan Title=Floodplain
Program Version=6.00
Short Identifier=Floodplain
Geom File=g01
Flow File=f01
Subcritical Flow
K Sum by GR= 0
Std Step Tol= 0.01
Critical Tol= 0.01
Num of Std Step Trials= 20
Max Error Tol= 0.3
Flow Tol Ratio= 0.001
Split Flow NTrial= 30
Split Flow Tol= 0.02
Split Flow Ratio= 0.02
Log Output Level= 0
Friction Slope Method= 1
Unsteady Friction Slope Method= 2
Unsteady Bridges Friction Slope Method= 1
Parabolic Critical Depth
Global Vel Dist= 0 , 0 , 0
Global Log Level= 0
CheckData=False
Encroach Param=-1 ,0,0, 0
Mapping Interval=1HOUR
Computation Time Step Use Courant=        0
Computation Time Step Use Time Series=    0
Computation Time Step Count To Double=0
Computation Time Step Max Doubling=0
Computation Time Step Max Halving=0
Computation Time Step Residence Courant=0
Run HTab= 0
Run UNet= 0
Run Sediment= 0
Run PostProcess= 0
Run WQNet= 0
Run RASMapper=-1
UNET Theta= 0
UNET Theta Warmup= 0
UNET ZTol= 0
UNET ZSATol= 0
UNET MxIter= 0
UNET Max Iter WO Improvement= 0
UNET MaxInSteps= 0
UNET DtIC= 0
UNET DtMin= 0
UNET MaxCRTS= 0
UNET WFStab= 0
UNET SFStab= 0
UNET WFX= 1
UNET SFX= 1
UNET Gravity=32.174
UNET 1D Methodology=Finite Difference
UNET DSS MLevel= 1
UNET Pardiso=0
UNET DZMax Abort= 0
UNET Use Existing IB Tables= 0
UNET Froude Reduction=False
UNET Froude Limit= 0
UNET Froude Power= 0
UNET D1 Cores= 0
UNET WindReference=Eulerian
UNET WindDragFormulation=Hsu (1988)
UNET D2 Coriolis=0
UNET D2 Cores= 0
UNET D2 Theta= 1
UNET D2 Theta Warmup= 1
UNET D2 Z Tol= 0.01
UNET D2 Volume Tol= 0.01
UNET D2 Max Iterations= 20
UNET D2 Equation= 0
UNET D2 RampUpFraction=0.1
UNET D2 TimeSlices= 1
UNET D2 Turbulence Formulation=Non-Conservative (original)
UNET D2 Eddy Viscosity=0.3
UNET D2 Transverse Eddy Viscosity=0.1
UNET D2 Smagorinsky Mixing=0
UNET D2 BCVolumeCheck=0
UNET D2 Cores=0
UNET D2 SolverType=PARDISO (Direct)
UNET D2 Minimum Iterations= 2147483647
UNET D2 Maximum Iterations= 2147483647
UNET D2 Restart Number= 10
UNET D2 Relaxation Coeff=1.3
UNET D2 SOR Precondition Iterations= 10
UNET D2 ILUT Maximum Fill= 8
UNET D2 ILUT Tolerance=1E-08
UNET D1D2 MaxIter= 0
UNET D1D2 ZTol=0.01
UNET D1D2 QTol=0.1
UNET D1D2 MinQTol=1
Write IC File= 0
Write IC File at Fixed DateTime=0
Write IC File at Sim End=0
Echo Input=False
Echo Parameters=False
Echo Output=False
Write Detailed= 0
HDF Write Warmup=0
HDF Write Time Slices=0
HDF Flush=0
HDF Compression= 1
HDF Chunk Size= 1
HDF Spatial Parts= 1
HDF Use Max Rows=0
HDF Fixed Rows= 1
Calibration Method= 0
Calibration Iterations= 20
Calibration Max Change=0.05
Calibration Tolerance=0.2
Calibration Maximum=1.5
Calibration Minimum=0.5
Calibration Optimization Method= 1
WQ AD Non Conservative
WQ ULTIMATE=-1
WQ Max Comp Step=1HOUR
WQ Output Interval=15MIN
WQ Output Selected Increments= 0
WQ Output face flow=0
WQ Output face velocity=0
WQ Output face area=0
WQ Output face dispersion=0
WQ Output cell volume=0
WQ Output cell surface area=0
WQ Output cell continuity=0
WQ Output cumulative cell continuity=0
WQ Output face conc=0
WQ Output face dconc_dx=0
WQ Output face courant=0
WQ Output face peclet=0
WQ Output face adv mass=0
WQ Output face disp mass=0
WQ Output cell mass=0
WQ Output cell source sink temp=0
WQ Output nsm pathways=0
WQ Output nsm derived pathways=0
WQ Create Restart=0
WQ Fixed Restart=0
WQ System Summary=0
WQ Write To DSS=0
Sorting and Armoring Iterations= 10
XS Update Threshold= 0.02
Bed Roughness Predictor= 0
Hydraulics Update Threshold= 0.02
Energy Slope Method= 1
Volume Change Method= 1
Sediment Retention Method= 0
Sediment TS Multiplier= 1
Warm Up Method= 0
XS Weighting Method= 0
Number of US Weighted Cross Sections= 1
Number of DS Weighted Cross Sections= 1
Upstream XS Weight=0
Main XS Weight=1
Downstream XS Weight=0
Number of DS XS's Weighted with US Boundary= 1
Upstream Boundary Weight= 1
Weight of XSs Associated with US Boundary= 0
Number of US XS's Weighted with DS Boundary= 1
Downstream Boundary Weight= 0.5
Weight of XSs Associated with DS Boundary= 0.5
Percentile Method= 0
Sediment Output Level= 3
Mass or Volume Output= 0
Output Increment Type= 1
Profile and TS Output Increment= 1
Transport Output Increment 1
XS Output Flag= 0
XS Output Increment= 10
Read HDF5 Sediment Hotstart= 0
Sediment Hotstart Type= 0
Write Gradation File= 0
Read Gradation Hotstart= 0
Write HDF5 File= 1
Write Binary Output= 1
Write DSS Sediment File= 0
DSS Sediment Output Type= 1
SV Curve= 0
Specific Gage Flag= 0
Subcell Erosion Methods= 0
Subcell Deposition Methods= 0
Advection Scheme= 1
Matrix Solver= 0
Implicit Weighting Factor= 1
Maximum Outer Loop Convergence Iterations= 5
Convergence Maximum Absolute= 0.001
Convergence RMSE= 0.0001
Grain Fractions Max Abs Error= 0.001
Max Subgrid Regions= 1
Max Subgrid Length Scale= 3.402823E+38
Initial Layer Thickness= 3.402823E+38
Min Layer Thickness= 3.402823E+38
Max Layer Thickness= 3.402823E+38
Number of Layers= 5

--- RFKTEACK.f01 (steady flow) ---

Flow Title=Flow
Program Version=6.10
Number of Profiles= 6
Profile Names=01pct,10pct,04pct,02pct,0_2pct,01plus
River Rch & RM=RFKTEACK,Main            ,8724
     760     406     537     645    1060    1120
River Rch & RM=RFKTEACK,Main            ,5313
     881     474     625     749    1220    1300
River Rch & RM=RFKTEACK,Main            ,3
    1630     896    1170    1390    2230    2410
Boundary for River Rch & Prof#=RFKTEACK,Main            , 1
Up Type= 0
Dn Type= 1
Dn Known WS=3417.7
Boundary for River Rch & Prof#=RFKTEACK,Main            , 2
Up Type= 0
Dn Type= 1
Dn Known WS=3416.3
Boundary for River Rch & Prof#=RFKTEACK,Main            , 3
Up Type= 0
Dn Type= 1
Dn Known WS=3417
Boundary for River Rch & Prof#=RFKTEACK,Main            , 4
Up Type= 0
Dn Type= 1
Dn Known WS=3417.3
Boundary for River Rch & Prof#=RFKTEACK,Main            , 5
Up Type= 0
Dn Type= 1
Dn Known WS=3418.5
Boundary for River Rch & Prof#=RFKTEACK,Main            , 6
Up Type= 0
Dn Type= 1
Dn Known WS=3418.7
DSS Import GetInterval= 0
DSS Import GetPeak= 0
DSS Import FillOption= 0

--- RFKTEACK.g01 (geometry) ---

Geom Title=Geometry
Program Version=6.10

River Reach=RFKTEACK        ,Main
Reach XY= 30
2204203.83690989 496543.403956892204070.27057597496530.758640975
2203903.13114648496370.5309430662203497.76548739496531.436133057
2202985.59820464496429.7900108992202876.27296397496572.522993147
2202747.88214463496573.3651830552202595.17116398496686.582148224
2202193.68869922496664.4988590632201938.03593031496829.203897317
2201769.10490271496836.8984486462201292.23348114 497101.90677689
2201230.10499647497208.4551202212201010.08279872497141.623889059
2200915.79296106497200.0443758962200277.30867372497244.803800806
2199872.04308005497618.9749684782199549.85507613497708.359960318
2199329.92835064497875.2457813922199236.64047948498166.559503227
2199014.63829881498056.4255371392198919.92293705 498075.18042089
 2198841.2469133498182.1569129822198830.26793264498361.829125807
2198501.97331364498530.7247853882198282.16675395498830.842444056
2198024.81809998498682.3370149732197631.84086755498988.711402223
2197507.39262563 499188.870450722197302.95077731499107.273829147

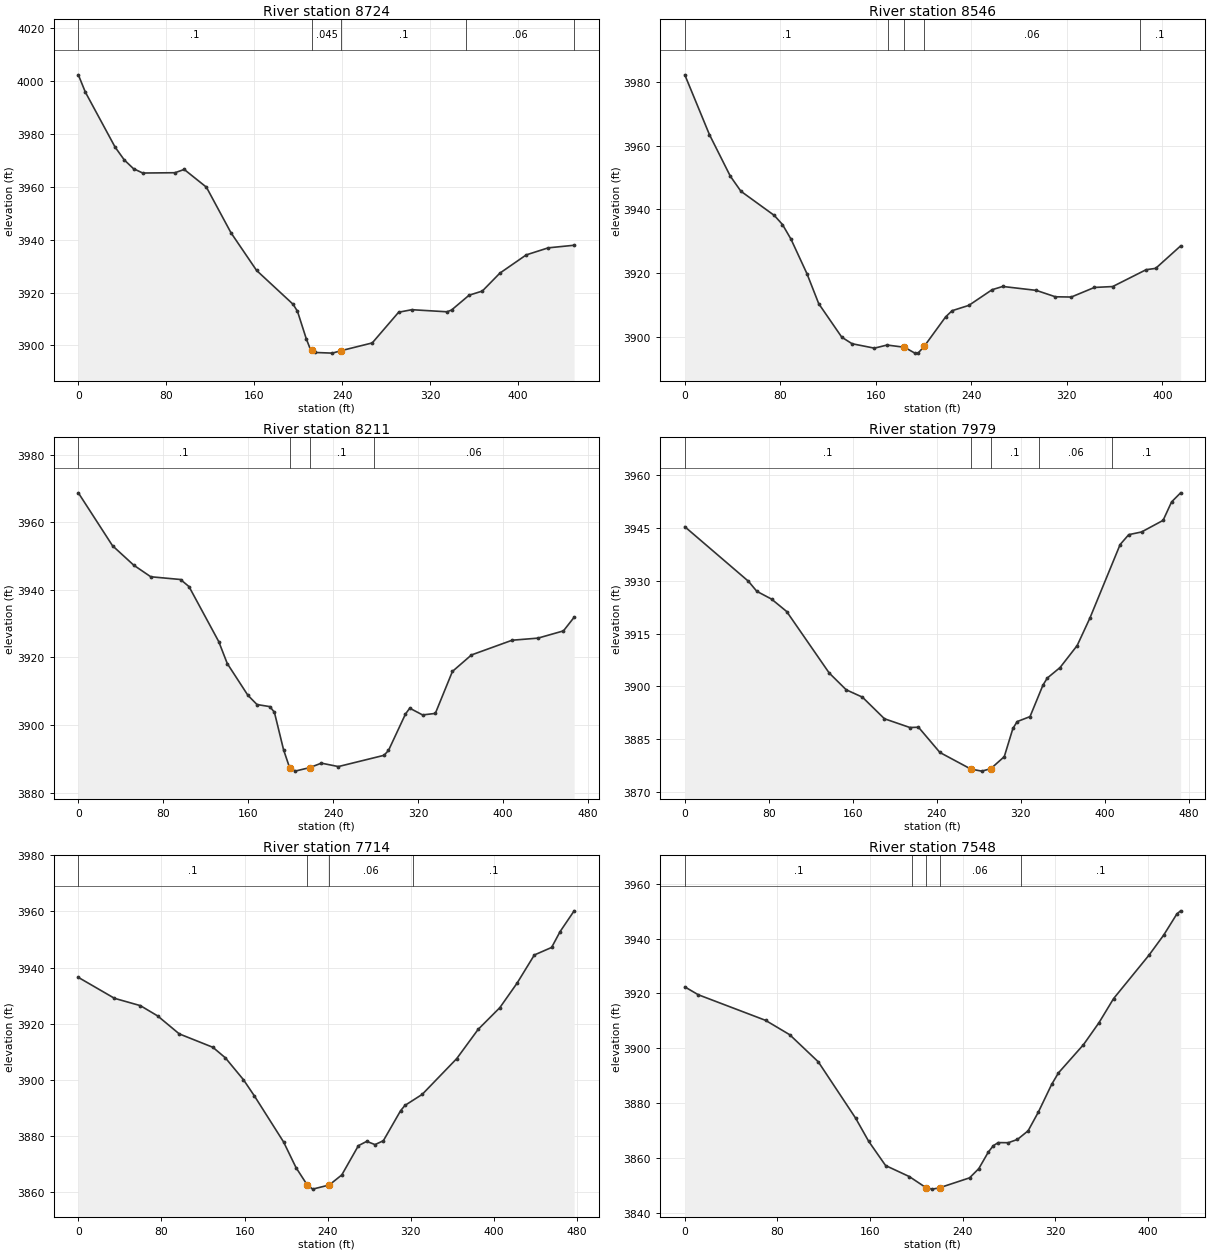
Type RM Length L Ch R = 1 ,8724    ,166.3,178.6,190.5
XS GIS Cut Line= 3
2204242.08507568496329.248106701     2204193.837496484.034717121
2204202.25616005496772.718559552
#Sta/Elev= 30
       0 4002.46     6.4  3995.9    33.4 3975.12    41.8 3970.23    50.2 3966.92
    58.6 3965.28    87.9  3965.4    96.3 3966.64   116.5 3959.92   138.8 3942.69
   162.1 3928.41   195.3  3915.6   199.3 3912.94   207.3 3902.54   211.3 3898.28
   212.2 3898.15   215.3 3897.35     231  3897.1   239.2 3898.05   267.3 3900.96
   291.3 3912.58   303.3 3913.54   335.3 3912.75   339.4 3913.41   355.4 3919.03
   367.4 3920.59   383.4 3927.39   407.4  3934.3   427.4 3936.96   450.9 3937.94
#Mann= 5 ,-1,0
       0      .1       0   212.2    .045       0   239.2      .1       0
  352.13     .06       0  450.94      .1       0
Bank Sta=212.2,239.2
XS Rating Curve= 0 ,0
Exp/Cntr=0.3,0.1

Type RM Length L Ch R = 1 ,8546    ,347.4,334.4,322.3
XS GIS Cut Line= 3
2204131.96625402496328.7742037312204008.64476105496535.879001086
2204013.35168826496710.035307952
#Sta/Elev= 30
       0 3982.27    20.6 3963.53    38.1 3950.47      47 3945.72      75 3938.12
    81.8 3935.28    88.9 3930.71   102.3 3919.86   112.2 3910.41   131.5  3899.9
   140.1 3897.85   158.8 3896.46   169.4 3897.44     184 3896.74   192.7  3894.9
   195.6 3894.98   200.7 3897.12   218.5 3906.29   223.9 3908.22   237.9 3909.89
   257.4 3914.81   266.3 3915.83   294.4  3914.6   310.4 3912.59   323.7 3912.51
   343.1 3915.52   358.4  3915.8   386.4 3921.09   394.4 3921.51   415.3 3928.56
#Mann= 5 ,-1,0
       0      .1       0     170     .06       0     184    .045       0
   200.7     .06       0  381.04      .1       0
Bank Sta=184,200.7
XS Rating Curve= 0 ,0
Exp/Cntr(USF)=0,0
Exp/Cntr=0.3,0.1

Type RM Length L Ch R = 1 ,8211    ,228.7,231.9,233.9
XS GIS Cut Line= 4
2203753.72133024 496204.995940872203752.63079475 496383.36677487
2203793.43839448496486.8410403622203777.13843506496663.247143153
#Sta/Elev= 30
       0 3968.69    32.2 3953.03    52.2 3947.27    68.2 3943.85    96.2 3943.04
   104.2 3940.94   132.2 3924.66   140.2 3918.18   159.6 3908.79   168.2 3906.04
   180.3 3905.42   184.6 3903.75   193.2 3892.67   198.9 3887.36   204.1 3886.33
  217.993887.387   228.8 3888.69   244.8 3887.68   287.8 3891.01     292 3892.45
     308 3903.23     312 3904.96   324.1 3902.96   336.1 3903.41   352.2 3915.84
   370.1 3920.71   408.4 3925.07   432.7 3925.69   456.7 3927.83   466.8 3931.88
#Mann= 4 ,-1,0
       0      .1       0   198.9    .045       0  217.99      .1       0
  278.37     .06       0
Bank Sta=198.9,217.99
XS Rating Curve= 0 ,0
Exp/Cntr=0.3,0.1

Type RM Length L Ch R = 1 ,7979    ,260.1,265,265.6
XS GIS Cut Line= 3
2203586.37179991496241.2668079632203553.74415113496455.782291512
 2203605.5961568496705.577927861
#Sta/Elev= 30
       0 3945.28    60.6 3929.81    68.6 3926.96    82.6 3924.76      97 3921.24
   137.5  3903.8   153.7 3899.04   169.1 3896.96   190.1 3890.83   214.3 3888.35
   222.5 3888.43   242.9 3881.27   272.4 3876.56   282.7 3875.98   291.3 3876.66
   304.2 3880.09   312.4 3888.08   316.5 3890.03   328.7 3891.44     341 3900.35
   345.1 3902.36   357.3 3905.35   373.6 3911.59   385.8 3919.43   414.5 3940.23
   422.7 3943.03   434.9 3943.79   455.4 3947.08   463.5 3952.32   472.1 3954.89
#Mann= 5 ,-1,0
       0      .1       0   272.4    .045       0   291.3      .1       0
  336.98     .06       0  406.98      .1       0
Bank Sta=272.4,291.3
XS Rating Curve= 0 ,0
Exp/Cntr(USF)=0,0
Exp/Cntr=0.3,0.1

Type RM Length L Ch R = 1 ,7714    ,165.6,166.2,163.9
XS GIS Cut Line= 4
 2203351.0208336496251.6543216832203322.37507685496354.072677911
2203319.50611121496540.0291250522203368.65081713496718.129839296
#Sta/Elev= 30
       0  3936.5    34.8 3929.03    59.7 3926.42    76.3 3922.76    97.1 3916.35
   129.5 3911.56   141.5  3907.8   158.9    3900   169.5 3894.18   197.5 3877.81
   209.5 3868.64  220.033862.608   225.5 3860.99   241.4 3862.46   253.5 3866.05
   269.5 3876.49   277.5 3878.02   285.5 3876.87   293.5 3878.25   310.1 3888.96
   314.3 3890.85   330.9 3894.78   364.1 3907.53   384.7 3917.95   405.6 3925.71
   422.2 3934.46   438.8 3944.49   455.4 3947.17   463.6 3952.84   477.1 3960.23
#Mann= 4 ,-1,0
       0      .1       0  220.03    .045       0   241.4     .06       0
  322.33      .1       0
Bank Sta=220.03,241.4
XS Rating Curve= 0 ,0
Exp/Cntr=0.3,0.1

Type RM Length L Ch R = 1 ,7548    ,386.5,380,373
XS GIS Cut Line= 4
2203208.37911535496289.9958716252203158.83576682496469.494695118
2203158.46518255496543.4626900462203222.92525323 496698.65784388
#Sta/Elev= 30
       0 3922.39    11.6 3919.52    69.7 3910.18    90.6 3904.93   115.3 3895.03
   147.6 3874.43   158.8 3866.03   173.4 3857.19   193.9 3853.16   208.4 3849.09
   213.9 3848.58220.0308 3849.08   245.9 3852.69   253.9 3856.06     262 3862.02
   266.4 3864.42   270.7 3865.56   279.4 3865.52   287.3 3866.72   296.5 3869.87
   305.4 3876.75   316.8 3886.78   322.7    3891   344.3  3901.3   357.7 3909.32
   370.3 3918.11     401 3934.03   413.6  3941.3     425 3949.03   428.2 3950.14
#Mann= 5 ,-1,0
       0      .1       0  196.21     .06       0   208.4    .045       0
220.0308     .06       0  290.18      .1       0
Bank Sta=208.4,220.0308
XS Rating Curve= 0 ,0
Exp/Cntr(USF)=0,0
Exp/Cntr=0.3,0.1

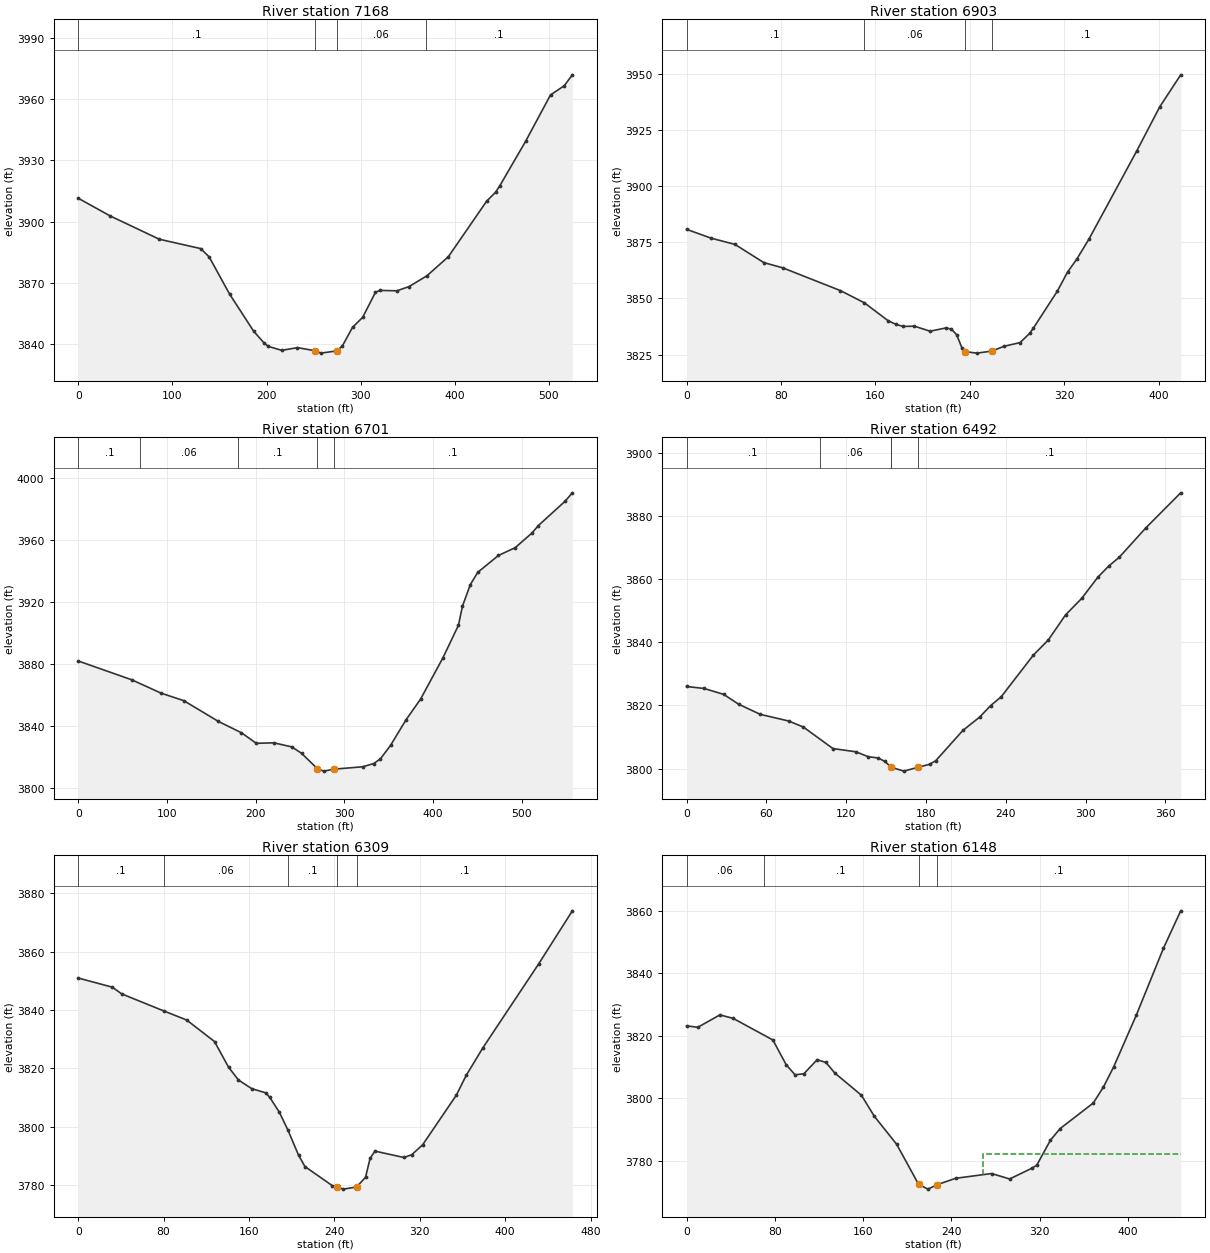
Type RM Length L Ch R = 1 ,7168    ,263.8,265.1,264.7
XS GIS Cut Line= 3
2202823.29478797496327.223348461 2202815.2865465496466.096111058
2202999.96833611496804.842973145
#Sta/Elev= 30
       0 3911.47      34 3902.79    86.1 3891.41   130.2 3886.81   139.1 3882.72
   160.8 3864.53   186.3  3846.4   197.3 3840.67   201.8 3838.96   216.2 3836.99
   232.9 3838.34   251.1 3836.84   257.9 3835.64   274.7 3836.75   280.6 3839.18
   291.4 3848.29   302.1 3853.13   315.7  3865.4   320.3 3866.35   338.5 3866.15
   351.4 3868.22   370.4 3873.51   393.2 3882.86   433.9 3910.08   443.3 3914.37
   447.9 3917.64   475.2 3939.32   501.7 3962.08   516.2 3966.52   524.9  3971.9
#Mann= 4 ,-1,0
       0      .1       0   251.1    .045       0   274.7     .06       0
   369.1      .1       0
Bank Sta=251.1,274.7
XS Rating Curve= 0 ,0
Exp/Cntr=0.3,0.1

Type RM Length L Ch R = 1 ,6903    ,195.6,202.2,210
XS GIS Cut Line= 3
2202642.69448395496424.7955188682202612.57014979 496597.06905485
2202722.71224657496814.529092073
#Sta/Elev= 30
       0 3880.77    20.7 3876.84      41 3874.05    65.4 3865.97    81.6  3863.6
   130.4 3853.48   150.6 3848.07   170.9 3840.03   177.7  3838.4   183.6 3837.53
   192.9 3837.66   206.4 3835.42   219.8 3836.88   224.3 3836.36   228.8 3833.87
   233.3 3828.01     236 3826.31   246.1 3825.65   258.53826.559   269.2 3828.73
   282.6 3830.34   290.8 3834.51   293.7 3836.65     314 3853.11     323 3861.89
   330.5 3867.38   340.9 3876.37   381.3 3915.52   400.9 3935.27   418.7 3949.55
#Mann= 4 ,-1,0
       0      .1       0     150     .06       0     236    .045       0
   258.5      .1       0
Bank Sta=236,258.5
XS Rating Curve= 0 ,0
Exp/Cntr(USF)=0,0
Exp/Cntr=0.3,0.1

Type RM Length L Ch R = 1 ,6701    ,200,209.2,218.5
XS GIS Cut Line= 4
 2202532.0413825496410.6593561152202450.13415389496584.867955554
2202454.17119676496821.2598467962202513.32754218496935.151263027
#Sta/Elev= 30
       0 3881.84    60.2 3869.76    93.7 3861.07     119  3856.3   158.1 3842.91
     184 3835.64   200.8 3828.83   220.8 3829.13   240.8  3826.5   251.8 3822.43
   269.6 3812.51   276.8  3810.9   288.4 3812.16   320.7  3813.7   333.2 3815.77
   340.8 3818.81   352.2 3827.46   369.8 3844.05   386.1 3857.29   411.2 3883.78
   428.8 3904.83   433.3 3917.05   442.2 3931.04   450.6 3938.95   473.9 3949.82
   492.7 3954.79   511.4 3964.08     519 3969.09     549  3984.7   557.3 3990.16
#Mann= 5 ,-1,0
       0      .1       0      70     .06       0     180      .1       0
   269.6    .045       0   288.4      .1       0
Bank Sta=269.6,288.4
XS Rating Curve= 0 ,0
Exp/Cntr=0.3,0.1

Type RM Length L Ch R = 1 ,6492    ,198.6,182.9,166
XS GIS Cut Line= 4
2202390.89466072496589.8690585462202265.87200567 496660.78533189
2202238.87239547496701.4535470892202261.78704996496879.069086392
#Sta/Elev= 30
       0    3826    13.2 3825.37    27.9 3823.51    39.1  3820.4    55.4 3817.19
    76.7 3815.09    87.8 3813.18   110.1 3806.36   127.3 3805.35   136.5 3803.81
   144.2 3803.37     149 3802.33     154 3800.43   163.4 3799.23   174.1 3800.45
   182.8  3801.4   187.4 3802.54   207.8 3812.11   220.5 3816.36   228.6 3819.93
   236.6 3822.75   260.8 3835.93   272.1 3840.75     285 3848.65   297.1 3853.84
   309.2 3860.52   317.3 3864.03   325.4 3866.88   345.5 3876.22   371.6 3887.25
#Mann= 5 ,-1,0
       0      .1       0     100     .06       0  153.74      .1       0
     154    .045       0   174.1      .1       0
Bank Sta=154,174.1
XS Rating Curve= 0 ,0
Exp/Cntr(USF)=0,0
Exp/Cntr=0.3,0.1

Type RM Length L Ch R = 1 ,6309    ,166.7,161,156.2
XS GIS Cut Line= 4
2202127.78560374496495.7147952422202058.85874032 496656.99045486
2202117.42150917 496777.031482362202238.04449477496872.866006976
#Sta/Elev= 30
       0 3850.91      32 3847.77    40.7 3845.48    80.1 3839.64   101.6 3836.52
   127.7 3829.13   140.8 3820.38   150.1 3815.96   162.5 3812.99   175.6 3811.56
   179.5 3809.98   188.5 3804.87   196.6 3798.67   206.4 3790.19   212.4 3786.28
   237.9 3779.76   242.5 3779.29   248.3 3778.53  260.85 3779.26   269.2 3782.61
   273.5 3789.12     278 3791.57   305.1 3789.38   312.5 3790.33   322.7 3793.73
   354.2  3810.7   363.6 3817.58   379.3 3827.07   431.4 3855.75     463 3873.96
#Mann= 5 ,-1,0
       0      .1       0    80.1     .06       0   196.6      .1       0
   242.5    .045       0  260.85      .1       0
Bank Sta=242.5,260.85
XS Rating Curve= 0 ,0
Exp/Cntr=0.3,0.1

Type RM Length L Ch R = 1 ,6148    ,189.5,192.3,192.7
XS GIS Cut Line= 4
2201957.61272101496599.0774964762201946.47711133496794.083069502
2201987.05166878496847.6871561082202027.43919178497028.450122615
#Sta/Elev= 30
       0  3823.2    10.1 3822.73    30.2 3826.71    42.2 3825.59    78.2 3818.68
    90.2  3810.8    98.3 3807.53   106.3 3807.88   118.3 3812.36   126.3 3811.49
   134.3 3808.11   158.4 3801.02   170.1 3794.28   190.4  3785.3   210.2 3772.53
   218.7 3770.96   227.3 3772.41   243.8 3774.42   276.4 3775.95   292.8 3774.21
   313.3 3777.71   317.4 3778.66   329.7 3786.58   338.4  3790.3   368.6 3798.52
   377.8 3803.65     387 3810.04   407.5 3826.57   432.2 3848.07   447.8    3860
#Mann= 4 ,-1,0
       0     .06       0      70      .1       0   210.2    .045       0
   227.3      .1       0
#XS Ineff= 2 , 0
                          268.42         3782.33
Permanent Ineff=
       F       F
Bank Sta=210.2,227.3
XS Rating Curve= 0 ,0
Exp/Cntr(USF)=0,0
Exp/Cntr=0.3,0.1

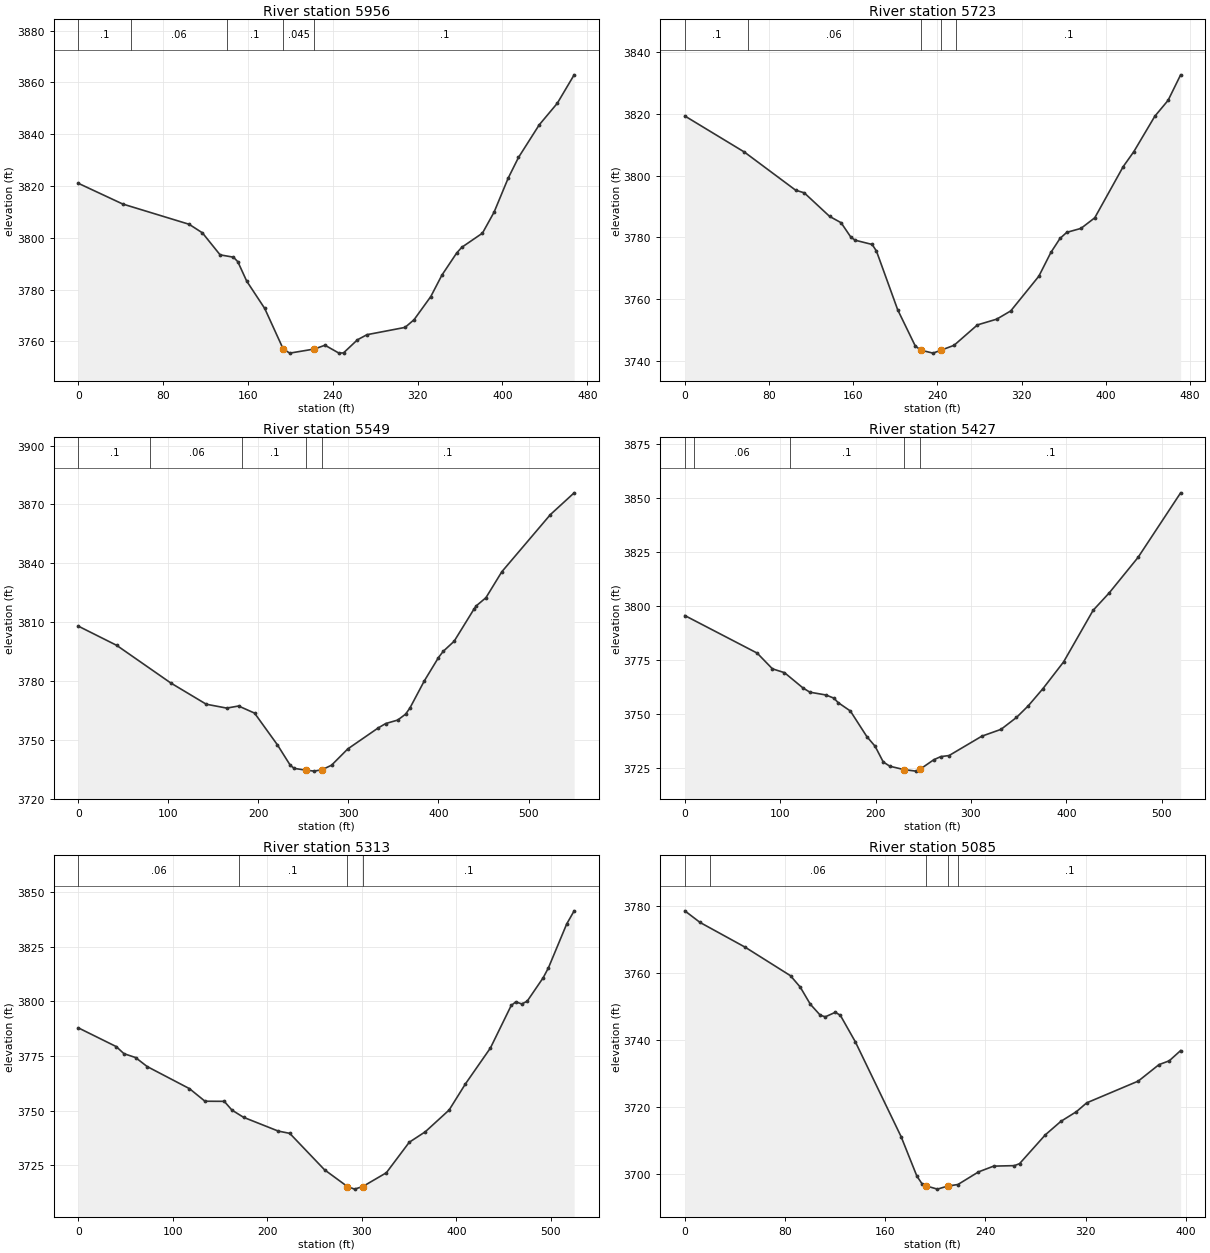
Type RM Length L Ch R = 1 ,5956    ,230.6,232.8,236.3
XS GIS Cut Line= 4
2201709.93005156496637.0529824082201758.55583249496799.444741361
2201809.93401611496915.9631220792201907.18557797 497056.33565948
#Sta/Elev= 30
       0 3821.02    41.9 3813.02   104.5  3805.2     117  3801.9   133.7  3793.4
   146.3  3792.5   150.4 3790.76   158.8 3783.25   175.8 3772.69   193.2 3757.07
   199.4 3755.46  222.64 3757.05   232.6 3758.51   245.7 3755.48   250.1 3755.55
   263.2  3760.6   272.2 3762.58   308.1 3765.39   316.6 3768.35   332.4 3777.31
   342.9 3785.59   356.8 3794.11   361.6 3796.31   381.1 3801.77   392.1  3809.9
   405.4 3823.03   415.1    3831   434.6 3843.56   451.7 3851.92   467.6  3862.9
#Mann= 5 ,-1,0
       0      .1       0      50     .06       0     140      .1       0
   193.2    .045       0  222.64      .1       0
Bank Sta=193.2,222.64
XS Rating Curve= 0 ,0
Exp/Cntr(USF)=0,0
Exp/Cntr=0.3,0.1

Type RM Length L Ch R = 1 ,5723    ,175.6,173.6,167.8
XS GIS Cut Line= 4
2201539.89310236496713.0282685622201570.03398013496918.811415443
2201596.84334203496998.6709081972201739.77883086497106.304156931
#Sta/Elev= 30
       0 3819.29    56.7  3807.6   105.3 3795.29   113.5 3794.43   137.6 3786.81
   148.5 3784.77   157.8 3780.09   161.9 3779.11     178 3777.74   182.1  3775.6
   202.3  3756.6   218.9 3744.97224.09293743.579   235.8  3742.6   243.1 3743.51
   255.8 3745.12     278 3751.72   296.4 3753.59   309.7 3756.25   336.4 3767.48
   347.8 3775.14   356.5 3779.69   362.9 3781.65   376.4 3782.93   389.5 3786.35
   416.6 3802.94   426.6 3807.73   446.6 3819.21   459.2 3824.34   471.1 3832.59
#Mann= 5 ,-1,0
       0      .1       0      60     .06       0224.0929    .045       0
   243.1     .06       0  257.98      .1       0
Bank Sta=224.0929,243.1
XS Rating Curve= 0 ,0
Exp/Cntr=0.3,0.1

Type RM Length L Ch R = 1 ,5549    ,121.3,122,122.8
XS GIS Cut Line= 4
2201387.42037016496790.6188980862201391.72483034  496932.6660842
2201486.42295442497134.975712908 2201606.9478396497275.588078961
#Sta/Elev= 30
       0 3807.94    42.6 3798.14   102.6 3778.97   142.1 3768.11   164.8 3766.14
     178  3767.2   195.7 3763.59   221.1 3747.41   235.4 3736.97   239.8 3735.38
   253.1 3734.48   261.9 3733.99   270.8 3734.74   281.2    3737   299.3 3745.33
   333.2 3756.06   341.4 3758.26   354.7 3760.03   363.5 3763.06   368.4 3766.27
   384.2 3779.96     400 3791.91   405.2 3795.06   417.4 3800.23   439.2 3816.46
     442  3818.3   452.7 3822.43   470.4  3835.7   524.3 3864.83   550.7 3875.93
#Mann= 5 ,-1,0
       0      .1       0      80     .06       0  182.11      .1       0
   253.1    .045       0   270.8      .1       0
Bank Sta=253.1,270.8
XS Rating Curve= 0 ,0
Exp/Cntr(USF)=0,0
Exp/Cntr=0.3,0.1

Type RM Length L Ch R = 1 ,5427    ,119.2,114.1,102.1
XS GIS Cut Line= 4
2201290.52192301496857.3818584832201297.84380979497008.003529287
2201363.74079076497172.2229898162201510.17852627497296.695064994
#Sta/Elev= 30
       0 3795.59    75.9 3778.22    91.9 3770.95   104.5 3769.19   123.9 3762.13
   131.2 3760.16     148 3758.87   156.4  3757.4   160.7 3755.38   173.6 3751.47
   190.9 3739.63   199.5  3735.2   208.1 3727.91     215 3725.95   229.6  3724.4
   242.3 3723.68   246.9 3724.62   261.1 3728.95   268.4 3730.39   277.1 3730.88
   311.5 3739.84   331.6 3742.99   347.8 3748.49   360.1 3753.84   375.6 3761.84
   397.2 3774.16   428.1 3797.97   445.1 3806.09   475.3 3822.48   519.9  3852.3
#Mann= 5 ,-1,0
       0      .1       0      10     .06       0     110      .1       0
   229.6    .045       0   246.9      .1       0
Bank Sta=229.6,246.9
XS Rating Curve= 0 ,0
Exp/Cntr(USF)=0,0
Exp/Cntr=0.3,0.1

Type RM Length L Ch R = 1 ,5313    ,214.1,228.1,245.6
XS GIS Cut Line= 4
2201178.49394968496901.8140744092201227.15608027497145.358812966
 2201311.2148137497199.9672737472201442.03848697497317.745657444
#Sta/Elev= 30
       0 3787.81    40.1 3779.24    48.3 3775.99    60.5 3774.24    72.8 3770.12
   117.6    3760     134 3754.25   154.4  3754.2   162.5  3750.2   174.8  3746.9
   211.5  3740.6   223.7 3739.55   260.5 3722.89   284.7 3715.23   292.3 3714.05
     301 3715.25   325.9 3721.54   350.1 3735.48   367.1 3740.28   392.3 3750.23
   409.6  3762.2     436  3778.6     458 3798.04   462.9 3799.71   469.1 3798.74
   474.8 3799.94   491.8 3810.71   497.4 3815.28   516.7 3835.31   524.6 3841.33
#Mann= 4 ,-1,0
       0     .06       0     170      .1       0   284.7    .045       0
     301      .1       0
Bank Sta=284.7,301
XS Rating Curve= 0 ,0
Exp/Cntr=0.3,0.1

Type RM Length L Ch R = 1 ,5085    ,171.5,164.2,156.5
XS GIS Cut Line= 4
2201090.05927552496944.9825093082201087.25021371497083.226268488
2201063.92358823497189.3458478832201099.49595607497333.982707648
#Sta/Elev= 30
       0 3778.46    12.2 3774.99    48.2 3767.61    84.4  3759.1    92.2 3755.69
   100.2 3750.61   108.2  3747.3   112.2 3746.84   120.2 3748.19   124.2 3747.29
   136.2 3739.36   172.7  3711.1   185.3 3699.32   189.4 3697.03   192.9 3696.37
   201.7 3695.43   209.9 3696.34   218.1 3696.81   234.5 3700.57   246.6 3702.29
   263.2 3702.44   267.3 3703.03   287.9 3711.64   300.3 3715.65   312.7 3718.54
   320.9 3721.17   362.1 3727.67   378.6 3732.57   386.8 3733.71   395.9 3736.77
#Mann= 5 ,-1,0
       0      .1       0      20     .06       0   192.9    .045       0
   209.9     .06       0  218.27      .1       0
Bank Sta=192.9,209.9
XS Rating Curve= 0 ,0
Exp/Cntr(USF)=0,0
Exp/Cntr=0.3,0.1

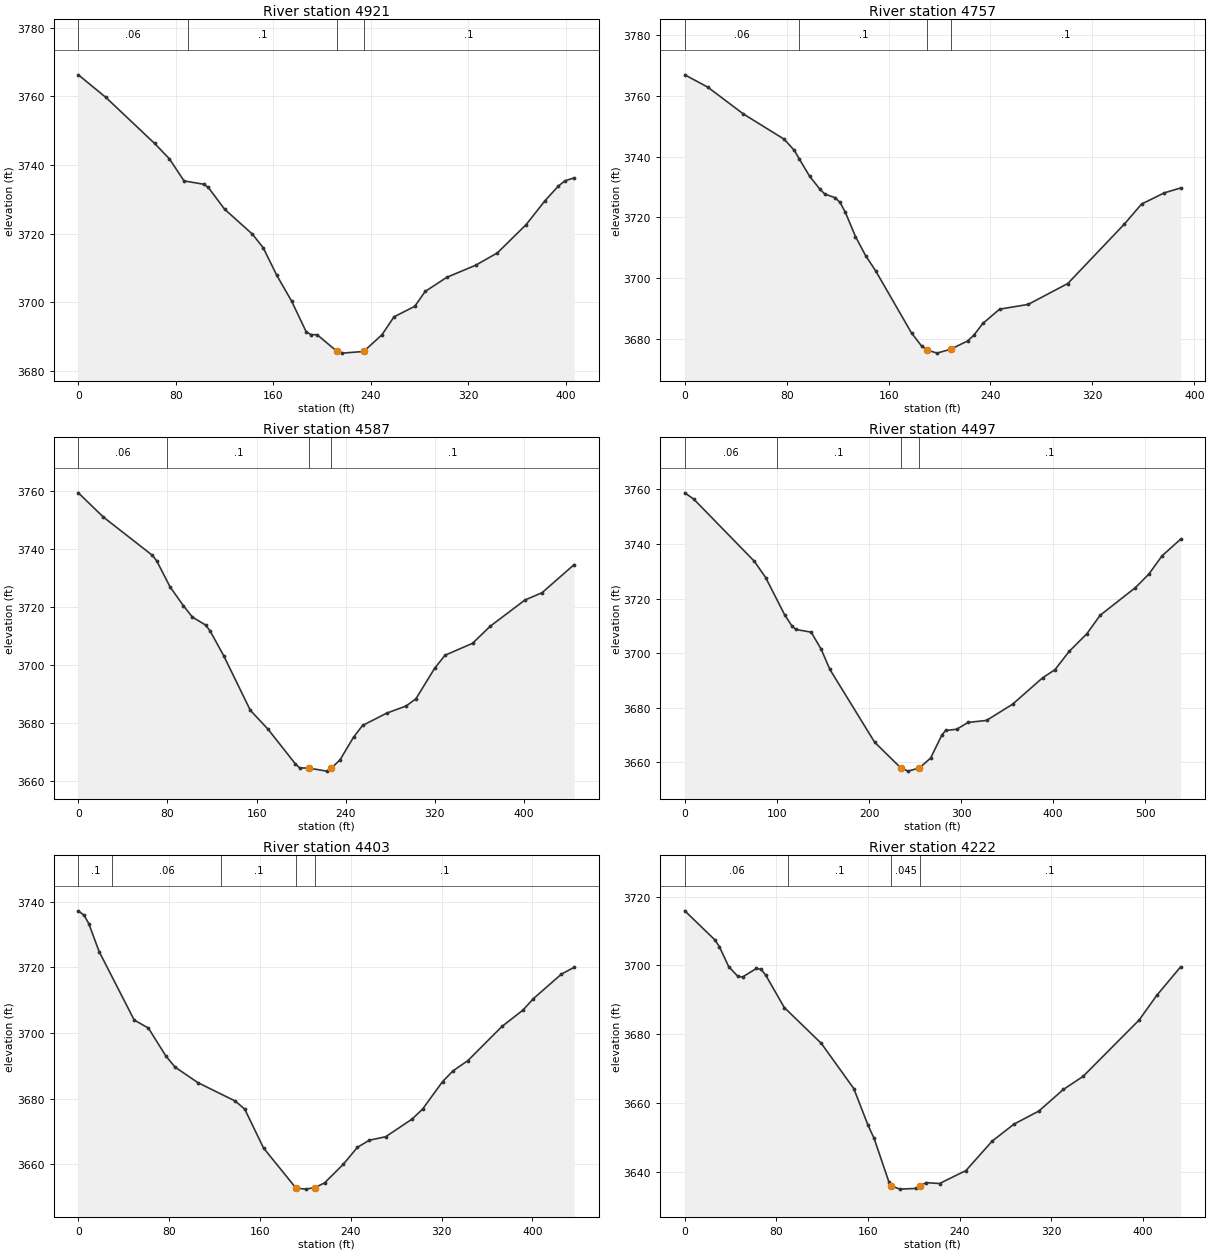
Type RM Length L Ch R = 1 ,4921    ,157.8,163.4,167.3
XS GIS Cut Line= 4
2200905.31099731496974.6810462212200918.15554322497166.431767245
 2200954.8542458497267.3531993632201033.75645637497339.833136975
#Sta/Elev= 30
       0 3766.26    22.5 3759.71    62.6 3746.25    74.7 3741.78    86.7 3735.35
   102.7 3734.38   106.5  3733.5   119.9 3727.13   142.8 3719.82   151.6 3715.89
   162.8 3707.82   174.9 3700.33   186.9 3691.37   190.9 3690.53   195.9 3690.51
   212.23685.657   216.4 3685.15  234.03 3685.63     249 3690.48   258.9 3695.71
     276 3698.81   284.5 3703.13   302.3 3707.26   325.9 3710.76   343.7 3714.36
   367.3  3722.6   382.8 3729.58   393.7 3733.83   399.1 3735.36   406.7 3736.23
#Mann= 4 ,-1,0
       0     .06       0      90      .1       0   212.2    .045       0
  234.03      .1       0
Bank Sta=212.2,234.03
XS Rating Curve= 0 ,0
Exp/Cntr(USF)=0,0
Exp/Cntr=0.3,0.1

Type RM Length L Ch R = 1 ,4757    ,172.3,170.3,169
XS GIS Cut Line= 3
2200771.20649101 496971.150876572200773.07762609497206.582392758
2200840.71834309497344.807625819
#Sta/Elev= 30
       0 3767.02      18 3762.97      46 3754.11      78 3745.79      86  3742.1
      90  3739.2      98 3733.57     106 3729.35     110 3727.66   118.1 3726.49
   121.9 3724.92   126.1 3721.65     134 3713.68     142 3707.36   149.8  3702.4
     178 3681.87     186 3677.52 190.4513676.247     198 3675.22208.71183676.511
     222 3679.22   226.9  3681.1     234 3685.01   247.2 3689.72   269.6 3691.29
   300.7 3698.18   345.2 3717.82   358.6 3724.38   376.4 3728.08   389.3  3729.7
#Mann= 4 ,-1,0
       0     .06       0      90      .1       0 190.451    .045       0
208.7118      .1       0
Bank Sta=190.451,208.7118
XS Rating Curve= 0 ,0
Exp/Cntr=0.3,0.1

Type RM Length L Ch R = 1 ,4587    ,90.5,90.3,89.8
XS GIS Cut Line= 4
 2200609.3416262496982.9344873252200600.91075933497162.511951595
2200611.02779958497239.2328400862200710.51202861497398.576223874
#Sta/Elev= 30
       0 3759.29    22.4 3750.96    66.3  3737.8    70.3 3735.89    82.3  3726.9
    94.3 3720.41   102.4 3716.46   114.4  3713.7   118.4 3711.61   130.4 3703.22
   154.4 3684.35   170.4 3677.78   194.6 3665.99   198.6 3664.53   207.33664.426
   222.8  3663.4     2273664.372     235 3667.37     247  3675.1   255.1 3679.14
   276.8 3683.38   294.2 3685.85     303 3688.34   319.7 3698.78   329.1 3703.33
   353.8 3707.44   369.7 3713.34   400.9 3722.37   416.2 3724.88     445 3734.57
#Mann= 4 ,-1,0
       0     .06       0      80      .1       0   207.3    .045       0
     227      .1       0
Bank Sta=207.3,227
XS Rating Curve= 0 ,0
Exp/Cntr(USF)=0,0
Exp/Cntr=0.3,0.1

Type RM Length L Ch R = 1 ,4497    ,94.9,93.9,92
XS GIS Cut Line= 4
2200533.59964947496971.7528483032200500.59878805497109.495574232
2200535.03446953 497327.588223622200632.60223373497473.939869919
#Sta/Elev= 30
       0 3758.72     9.7 3756.43    75.4 3733.68    87.8 3727.67   108.5 3713.97
   116.6 3709.79   120.7 3708.66   137.2 3707.68     148 3701.47   157.5 3694.03
   206.1 3667.35   234.5 3657.95   242.4 3656.76   254.7 3657.93   266.9 3661.55
     279 3669.93   283.1 3671.65   295.2  3672.1   307.4 3674.59   327.6 3675.34
   355.9 3681.28   388.4 3690.94   401.9 3693.93   417.2 3700.59   436.5 3707.09
   450.9 3713.85   489.3 3724.02   503.8 3728.94   518.2 3735.66   538.3 3741.75
#Mann= 4 ,-1,0
       0     .06       0     100      .1       0   234.5    .045       0
   254.7      .1       0
Bank Sta=234.5,254.7
XS Rating Curve= 0 ,0
Exp/Cntr(USF)=0,0
Exp/Cntr=0.3,0.1

Type RM Length L Ch R = 1 ,4403    ,185.6,180.6,173.4
XS GIS Cut Line= 4
2200405.93755908497035.9874068542200402.06354491497141.877127412
2200451.13439103497329.1211454732200535.07136464497437.593542143
#Sta/Elev= 30
       0 3737.22     5.2 3735.82     9.2 3733.32    18.3 3724.83    49.2 3703.97
    61.7 3701.53    77.2 3692.97    85.2 3689.64   105.3 3684.91   138.3 3679.29
   146.6 3676.82   163.1 3665.02   191.7 3652.81   200.3 3652.49   208.5 3652.98
   216.9 3654.39   233.4 3660.07   245.8 3665.22   256.3 3667.38   270.6 3668.43
   293.9  3673.8   303.2 3676.86   320.8 3685.22   329.9 3688.47   343.1 3691.62
   373.1 3702.01   391.6    3707   400.8 3710.48   425.4 3717.93   436.7 3720.03
#Mann= 5 ,-1,0
       0      .1       0      30     .06       0  125.96      .1       0
   191.7    .045       0   208.5      .1       0
Bank Sta=191.7,208.5
XS Rating Curve= 0 ,0
Exp/Cntr(USF)=0,0
Exp/Cntr=0.3,0.1

Type RM Length L Ch R = 1 ,4222    ,143.7,138.3,132.1
XS GIS Cut Line= 5
2200257.95112347497079.2709431492200235.50670197497227.578801893
2200240.63792611497243.6248004672200291.47645413497320.573544184
2200418.67784651497439.395005658
#Sta/Elev= 30
       0 3715.87    26.2 3707.44    30.2 3705.46    38.3 3699.66    46.4 3696.78
    50.5 3696.62    62.6 3699.12    66.7 3698.81    70.7 3697.15    86.9 3687.73
   119.3 3677.28   147.6 3664.15   160.1 3653.44   165.3  3649.7   178.3 3636.95
   180.5 3635.81   187.9 3634.88   202.3 3635.09   205.2  3635.8   210.9 3636.77
   222.5 3636.51   245.6 3640.29   268.5 3648.86   287.4 3653.76   309.3 3657.61
   330.7 3663.89   347.9 3667.69   396.9 3684.11   412.3 3691.29   433.1 3699.56
#Mann= 4 ,-1,0
       0     .06       0      90      .1       0   180.5    .045       0
   205.2      .1       0
Bank Sta=180.5,205.2
XS Rating Curve= 0 ,0
Exp/Cntr=0.3,0.1

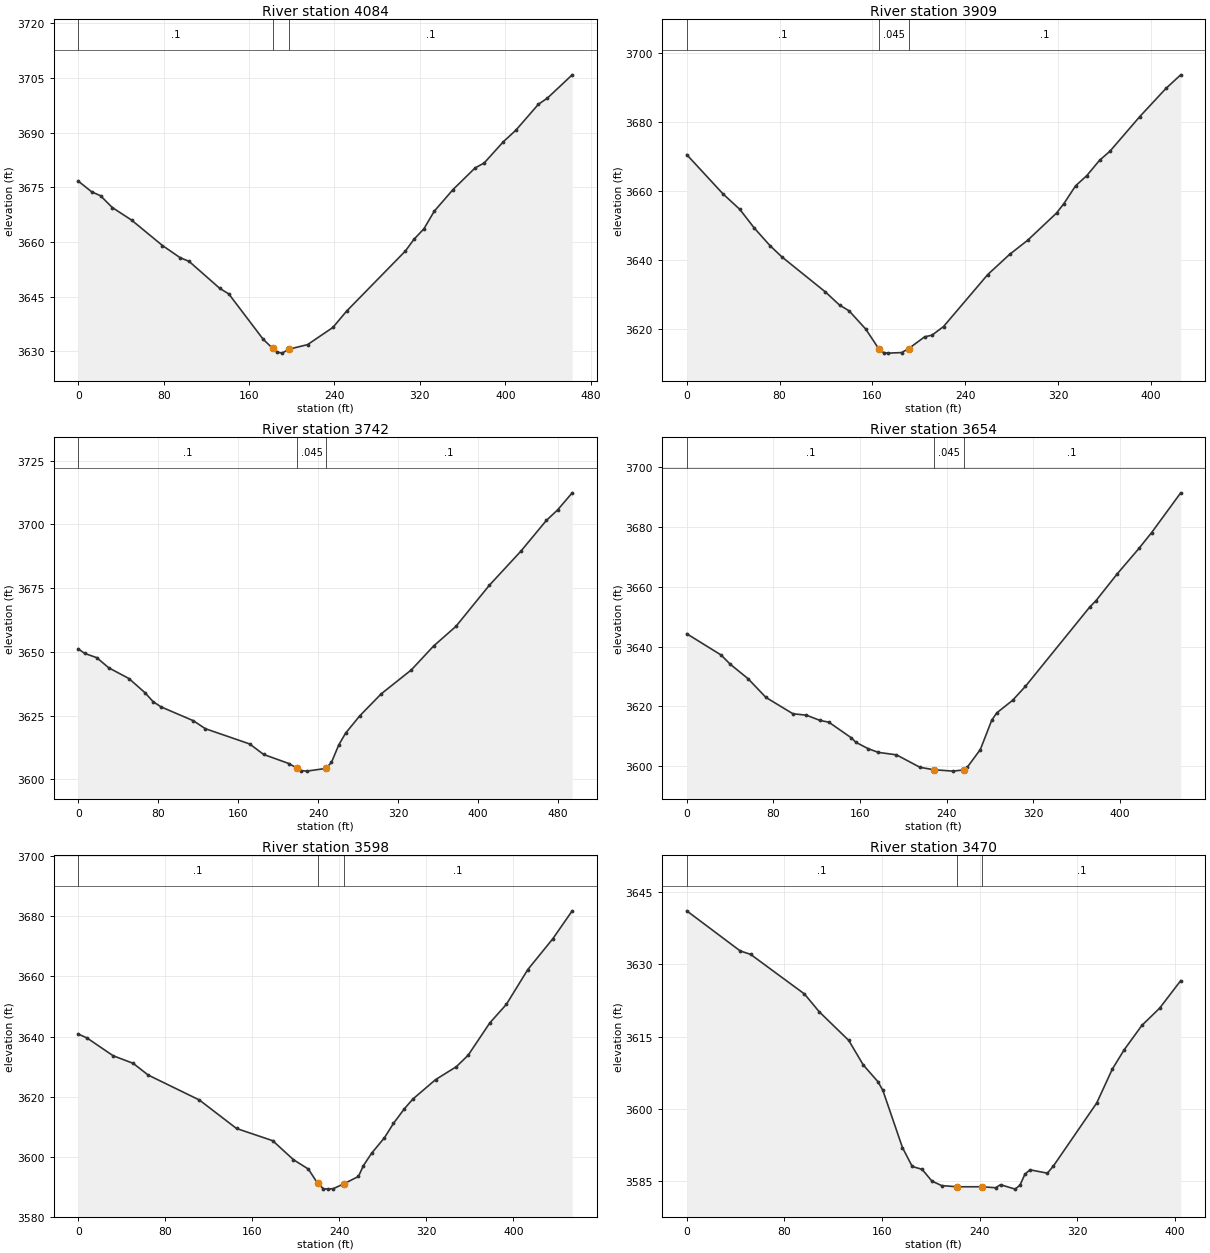
Type RM Length L Ch R = 1 ,4084    ,171.9,175.2,178.1
XS GIS Cut Line= 4
2200085.45156274497188.9359173772200124.96650725497337.698061381
  2200277.215264497435.323218384  2200398.084506497477.162571385
#Sta/Elev= 30
       0  3676.7    12.7 3673.74    20.9 3672.68    31.9 3669.45    49.9 3666.02
    78.9 3659.04    95.4 3655.71   103.8  3654.7   132.7 3647.26     141 3645.78
   173.2 3633.36     1823630.874   186.2 3629.81     191 3629.54   197.4 3630.62
   214.8 3631.87   238.5 3636.57   251.4 3641.06   306.4 3657.52   314.5 3660.75
   323.8 3663.62   333.5 3668.45   351.1 3674.39   371.8 3680.33   380.2 3681.65
   398.3 3687.52   409.9 3690.64     431 3697.75   439.5 3699.46   462.7 3705.83
#Mann= 3 ,-1,0
       0      .1       0     182    .045       0   197.4      .1       0
Bank Sta=182,197.4
XS Rating Curve= 0 ,0
Exp/Cntr(USF)=0,0
Exp/Cntr=0.3,0.1

Type RM Length L Ch R = 1 ,3909    ,167.9,166.6,165.1
XS GIS Cut Line= 3
2199967.65914618 497276.527875012199997.93557581497417.817879975
2200175.92428337497635.257692811
#Sta/Elev= 30
       0 3670.53    31.3  3659.1    45.7 3654.64    58.3 3649.16    71.7 3644.11
    81.8 3640.87   119.3 3630.69   131.6 3626.84   139.8 3625.18   154.2 3619.86
   165.5 3614.09   169.5 3613.06   173.3 3612.88     185 3613.04   191.1 3614.17
   204.9 3617.62   211.2 3618.08   221.2  3620.6   259.3 3635.71   278.1 3641.55
   293.6 3645.65   318.5 3653.55   324.9 3656.32   334.9 3661.46   344.6 3664.44
   355.6 3668.89   364.5 3671.51   390.1 3681.53   412.8 3689.77   425.5 3693.71
#Mann= 3 ,-1,0
       0      .1       0   165.5    .045       0   191.1      .1       0
Bank Sta=165.5,191.1
XS Rating Curve= 0 ,0
Exp/Cntr(USF)=0,0
Exp/Cntr=0.3,0.1

Type RM Length L Ch R = 1 ,3742    ,83.6,88,96.7
XS GIS Cut Line= 3
   2199853.27085497358.7973867312199873.07173734 497530.32505895
2200103.70805277497754.185955554
#Sta/Elev= 30
       0 3651.18     6.4 3649.39    18.5 3647.72    30.6 3643.72    50.7 3639.54
    66.8 3633.97    74.9 3630.46    82.9 3628.41   115.1    3623   127.2 3619.86
   171.5 3613.88   185.4 3609.78   210.8 3606.19   219.3 3604.28   222.7 3603.45
   228.5 3603.23   247.6 3604.28   253.3 3606.66   260.6 3613.51   267.4  3618.1
   281.5 3624.87   303.1 3633.55   333.1 3642.89   355.4 3652.26   377.8 3659.99
   411.1 3676.05   442.8 3689.49   468.2  3701.5   479.6 3705.69   494.1 3712.35
#Mann= 3 ,-1,0
       0      .1       0   219.3    .045       0   247.6      .1       0
Bank Sta=219.3,247.6
XS Rating Curve= 0 ,0
Exp/Cntr=0.3,0.1

Type RM Length L Ch R = 1 ,3654    ,57.5,56.4,55.4
XS GIS Cut Line= 4
  2199784.259599497406.6709185392199839.65039431497605.470759266
2199867.72518098497663.8966666552200014.92811648497776.195813326
#Sta/Elev= 30
       0 3644.28    31.7 3637.16      40 3634.13    56.6 3629.23    73.2 3622.93
    98.1 3617.47   110.6 3616.99     123 3615.25   131.3 3614.64   152.1 3609.39
   156.2 3607.92   167.6 3605.77     177 3604.53   193.7 3603.71   215.5 3599.52
   228.2 3598.72     246 3598.25   255.9 3598.67   259.3 3599.64   271.2 3605.49
   281.8 3615.37   286.5 3617.81     301 3621.97   312.9 3626.68   372.2  3653.2
     378 3655.34   397.5 3664.28   417.7 3672.86   429.4 3678.16   456.3 3691.49
#Mann= 3 ,-1,0
       0      .1       0   228.2    .045       0   255.9      .1       0
Bank Sta=228.2,255.9
XS Rating Curve= 0 ,0
Exp/Cntr(USF)=0,0
Exp/Cntr=0.3,0.1

Type RM Length L Ch R = 1 ,3598    ,121.8,128,134.6
XS GIS Cut Line= 3
2199688.23873204497457.2905924742199835.31052073497715.837176399
2199960.83676075497809.513474922
#Sta/Elev= 30
       0 3640.82       8 3639.53    32.1  3633.6    50.5 3631.08    64.3 3627.18
   111.3  3618.9   145.5 3609.42   178.8 3605.35   197.8 3599.05   211.6 3595.91
   220.13591.155   225.4 3589.38     230 3589.25   234.6 3589.44     2443590.971
   257.6 3593.48   262.2 3597.09   269.7 3601.19   281.5 3606.34   289.8 3611.11
   299.7 3615.92   307.6  3619.2   328.5 3625.66   347.6 3629.97   358.4 3633.76
   378.4 3644.55   393.5 3650.65   413.3 3662.27   436.2 3672.47   454.1 3681.79
#Mann= 3 ,-1,0
       0      .1       0   220.1    .045       0     244      .1       0
Bank Sta=220.1,244
XS Rating Curve= 0 ,0
Exp/Cntr(USF)=0,0
Exp/Cntr=0.3,0.1

Type RM Length L Ch R = 1 ,3470    ,83.7,85.9,85.6
XS GIS Cut Line= 3
2199668.92534025497465.0968259282199692.44745881497745.844692604
2199761.49625845497847.520947022
#Sta/Elev= 30
       0  3641.1    43.8 3632.78    52.3 3632.07    96.4 3623.86   108.5 3620.17
   132.7 3614.22   144.6 3609.13   156.6 3605.66   160.6 3603.88   176.7 3591.99
   184.7 3588.08   192.8 3587.48   200.8 3585.05   208.8 3584.11   221.6 3583.87
   241.9 3583.87     253 3583.67     257  3584.3     269 3583.38     273 3584.22
   276.9 3586.44   281.1 3587.39   295.4 3586.69   300.3 3588.17   335.8 3601.25
   348.6 3608.29   358.3 3612.28   372.8 3617.34   387.3  3620.9   404.6 3626.63
#Mann= 3 ,-1,0
       0      .1       0   221.6    .045       0   241.9      .1       0
Bank Sta=221.6,241.9
XS Rating Curve= 0 ,0
Exp/Cntr(USF)=0,0
Exp/Cntr=0.3,0.1