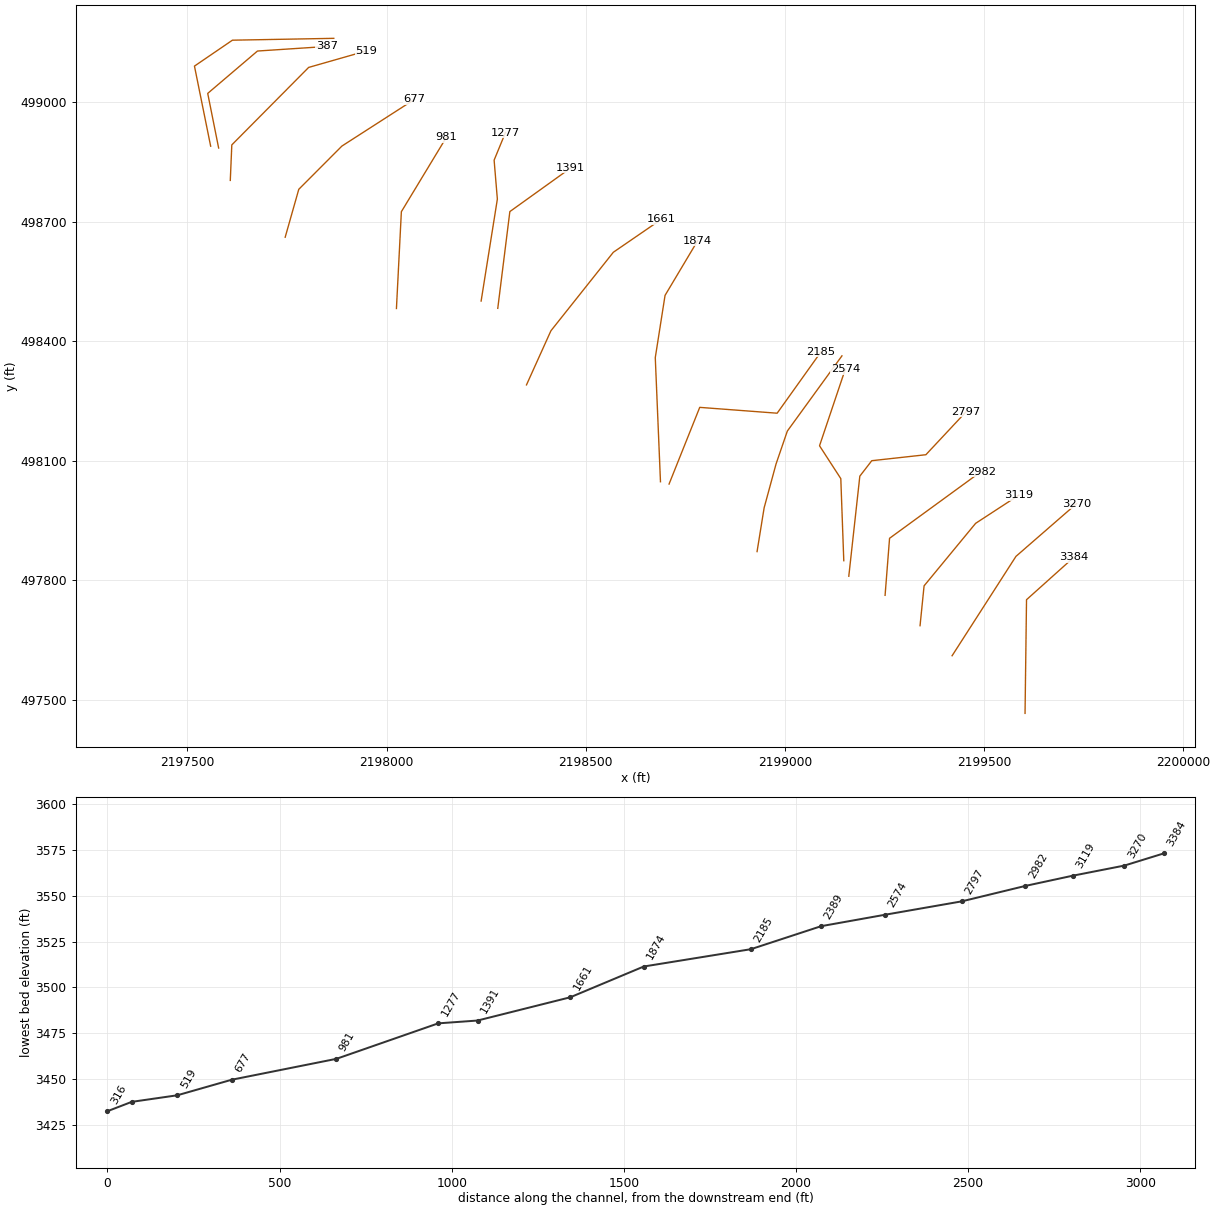
HEC-RAS study RFKTEACK.prj: RFKTEACK

--- RFKTEACK.g01 (geometry) --- (continued)

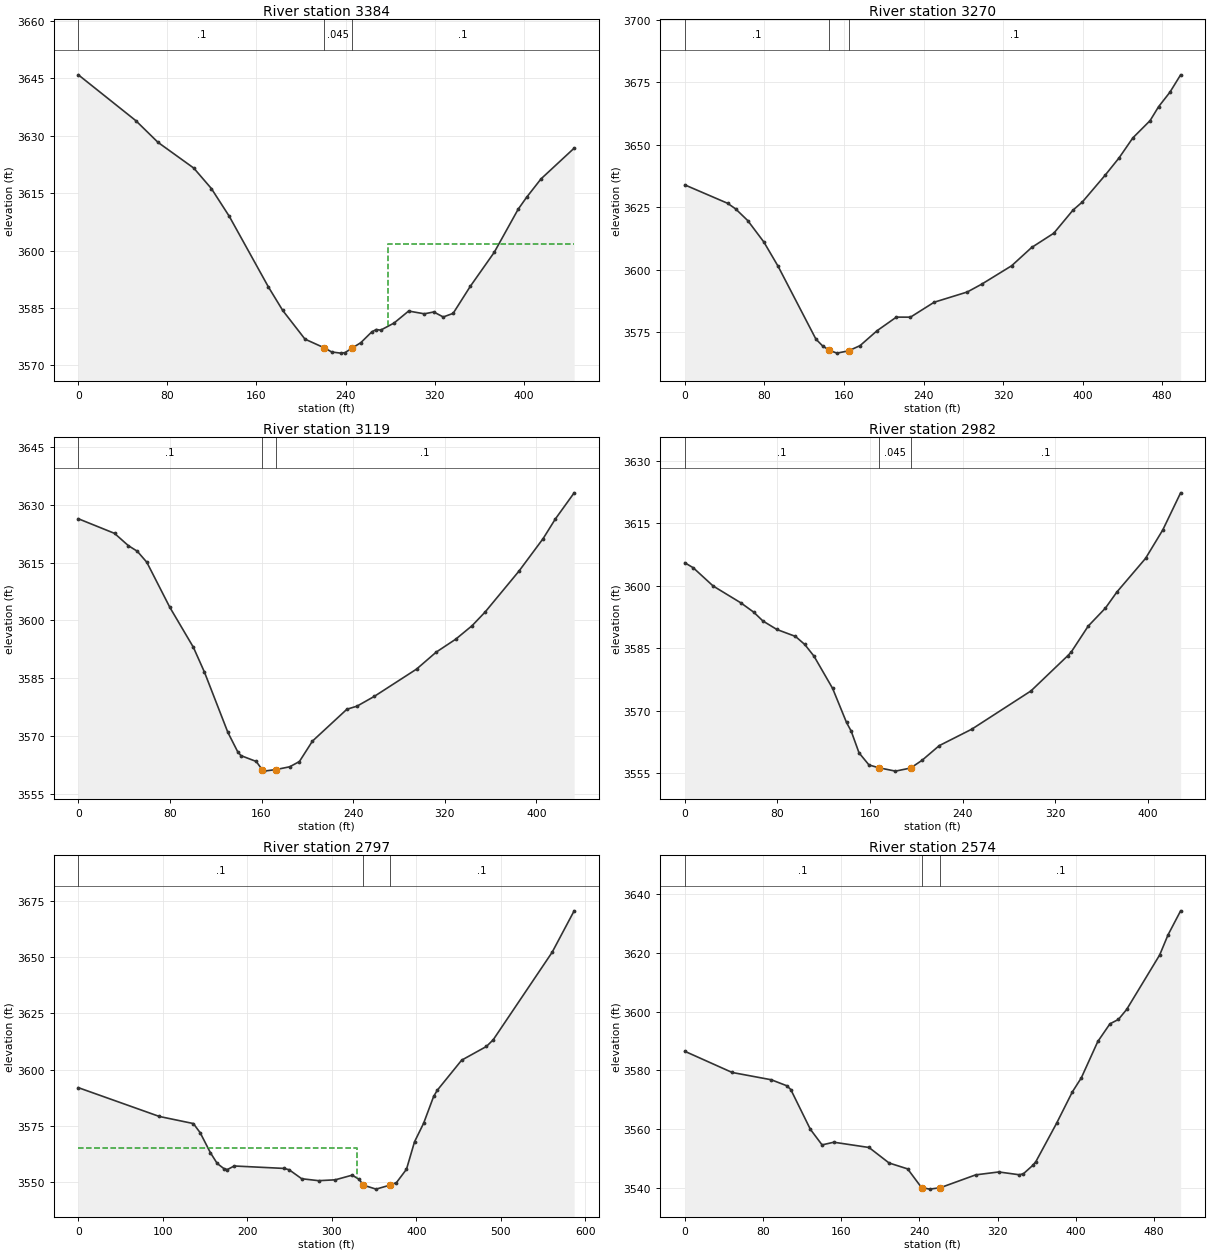
Type RM Length L Ch R = 1 ,3384    ,123.1,114.4,104.7
XS GIS Cut Line= 3
  2199602.770557497465.5798872742199606.48617773497750.939376423
2199725.62231895497857.768872801
#Sta/Elev= 30
       0 3645.95    51.6 3633.98    71.6 3628.29   103.7 3621.57   119.5 3616.23
   135.6 3608.96   170.8 3590.47   183.6 3584.36   203.6 3576.86   221.1 3574.56
   227.6  3573.5   235.6  3573.2   239.6 3573.33   245.8  3574.5   253.7 3575.92
   263.6 3578.75   267.6 3579.37   271.6 3579.21   283.6 3581.06   296.7  3584.2
   310.8 3583.48   319.3 3583.96   327.8 3582.65   336.7  3583.6   352.1 3590.66
   373.6 3599.55   395.1 3610.82   402.6  3613.9   415.6 3618.74   445.4 3626.78
#Mann= 3 ,-1,0
       0      .1       0   221.1    .045       0   245.8      .1       0
#XS Ineff= 2 , 0
                          277.89         3601.82
Permanent Ineff=
       F       F
Bank Sta=221.1,245.8
XS Rating Curve= 0 ,0
Exp/Cntr(USF)=0,0
Exp/Cntr=0.3,0.1

Type RM Length L Ch R = 1 ,3270    ,151.8,150.2,148.1
XS GIS Cut Line= 3
2199419.63807358 497610.281614542199579.95768475497859.730242002
 2199732.3350555497992.251792247
#Sta/Elev= 30
       0 3633.89      43 3626.53      51 3624.31    63.3  3619.6    79.5 3611.02
    93.8 3601.31   131.8 3572.17   138.5 3569.46145.39643567.657     153 3566.55
   164.6 3567.46   176.2 3569.55   193.3 3575.52   212.7 3580.96   226.9 3580.95
   250.7 3586.92     284 3591.02   298.7  3594.2   328.6 3601.52   348.7 3608.83
     371 3614.55   390.2 3623.75   399.8 3627.09   422.5 3637.71   436.6 3644.69
   450.5 3652.72   467.8 3659.61   476.3 3665.16   487.7 3670.96   498.5 3677.94
#Mann= 3 ,-1,0
       0      .1       0145.3964    .045       0   164.6      .1       0
Bank Sta=145.3964,164.6
XS Rating Curve= 0 ,0
Exp/Cntr=0.3,0.1

Type RM Length L Ch R = 1 ,3119    ,141.1,137,131.7
XS GIS Cut Line= 4
2199339.19386435 497685.718408872199349.28600756497785.722373423
2199478.64893419497942.6093269882199586.91010682498013.254329471
#Sta/Elev= 30
       0 3626.33    31.6 3622.55    43.7 3619.37    51.5 3617.92    59.8 3615.08
    79.9 3603.42   100.5 3593.06   110.2 3586.61   130.6 3571.05   139.1 3566.09
     142 3565.03   155.4 3563.51  160.55 3561.41     162 3561.01   172.4  3561.4
   184.6 3562.13   193.1 3563.49   204.5 3568.78   234.6 3577.03   243.4 3577.82
   258.5 3580.35   295.4 3587.41   312.6 3591.81   329.6 3595.15   343.9 3598.64
   355.3 3602.18   384.9 3612.78     406  3621.2   416.6 3626.24   433.1 3633.04
#Mann= 3 ,-1,0
       0      .1       0  160.55    .045       0   172.4      .1       0
Bank Sta=160.55,172.4
XS Rating Curve= 0 ,0
Exp/Cntr(USF)=0,0
Exp/Cntr=0.3,0.1

Type RM Length L Ch R = 1 ,2982    ,193.7,185,174.3
XS GIS Cut Line= 3
2199251.40497222497761.9054241062199262.64584921497905.143537102
2199492.62606814498072.756592475
#Sta/Elev= 30
       0 3605.47     7.3 3604.27    24.5 3599.89    48.4 3595.85    59.5 3593.62
    67.5 3591.49    79.5 3589.46    95.6 3587.79   103.6 3585.86   111.6 3583.05
   127.7  3575.3   139.7 3567.13   143.7 3565.07   150.5 3559.84   159.1 3556.93
   167.7 3556.25     182 3555.45   195.1  3556.2     205 3558.06   219.8 3561.57
   247.9 3565.52     299  3574.7   330.9 3583.18   333.8 3584.04   348.5 3590.28
   363.4 3594.61   373.3 3598.47     398 3606.52   412.9 3613.36   428.3 3622.26
#Mann= 3 ,-1,0
       0      .1       0   167.7    .045       0   195.1      .1       0
Bank Sta=167.7,195.1
XS Rating Curve= 0 ,0
Exp/Cntr(USF)=0,0
Exp/Cntr=0.3,0.1

Type RM Length L Ch R = 1 ,2797    ,181.8,223.6,260.7
XS GIS Cut Line= 5
2199160.30786045497809.8742909792199188.00148188498061.100124081
2199217.98371346498099.9100003452199353.81434631498114.898208109
2199455.10940177498223.161583847
#Sta/Elev= 30
       0 3592.01    95.9 3579.23   136.1 3576.09   144.2 3572.01   156.2 3563.21
   164.3 3558.39   172.3 3556.09   176.4 3555.68   184.4 3557.27   243.6 3556.18
   249.4  3555.6   264.3 3551.61   284.3 3550.75     304 3551.13   324.1  3553.2
   332.2 3551.34337.39443548.753   352.3    3547   368.4 3548.74   376.4 3549.88
   388.3 3555.82   397.8 3567.98   408.6 3576.24   420.4 3588.09   424.7 3590.85
   453.6 3604.21   482.9 3610.29   490.9 3613.24   560.6 3652.04   586.7 3670.45
#Mann= 3 ,-1,0
       0      .1       0337.3944    .045       0   368.4      .1       0
#XS Ineff= 2 , 0
          330.15 3565.27
Permanent Ineff=
       F       F
Bank Sta=337.3944,368.4
XS Rating Curve= 0 ,0
Exp/Cntr(USF)=0,0
Exp/Cntr=0.3,0.1

Type RM Length L Ch R = 1 ,2574    ,202.4,184.8,169.8
XS GIS Cut Line= 4
2199147.72648956497848.8575203022199140.23238568498054.945377054
2199086.83689552498137.380519755 2199151.4735415498329.416931728
#Sta/Elev= 30
       0 3586.53    48.4 3579.33    88.4 3576.85   104.4  3574.8   108.4 3573.52
   128.4 3560.01   140.4  3554.7   152.4 3555.61   188.4 3553.82   208.9 3548.55
   227.9 3546.54   242.2 3540.16   250.5 3539.66   261.3 3540.14   297.5 3544.51
   321.1  3545.5   342.2 3544.54   346.4 3544.91   355.9 3547.75   359.1 3549.04
   380.2 3562.03   396.4 3572.74   405.5 3577.48   422.4 3589.86   434.8 3595.86
   443.5 3597.37   451.9 3600.75   485.7  3619.3   494.2  3626.1   507.1 3634.29
#Mann= 3 ,-1,0
       0      .1       0   242.2    .045       0   261.3      .1       0
Bank Sta=242.2,261.3
XS Rating Curve= 0 ,0
Exp/Cntr(USF)=0,0
Exp/Cntr=0.3,0.1

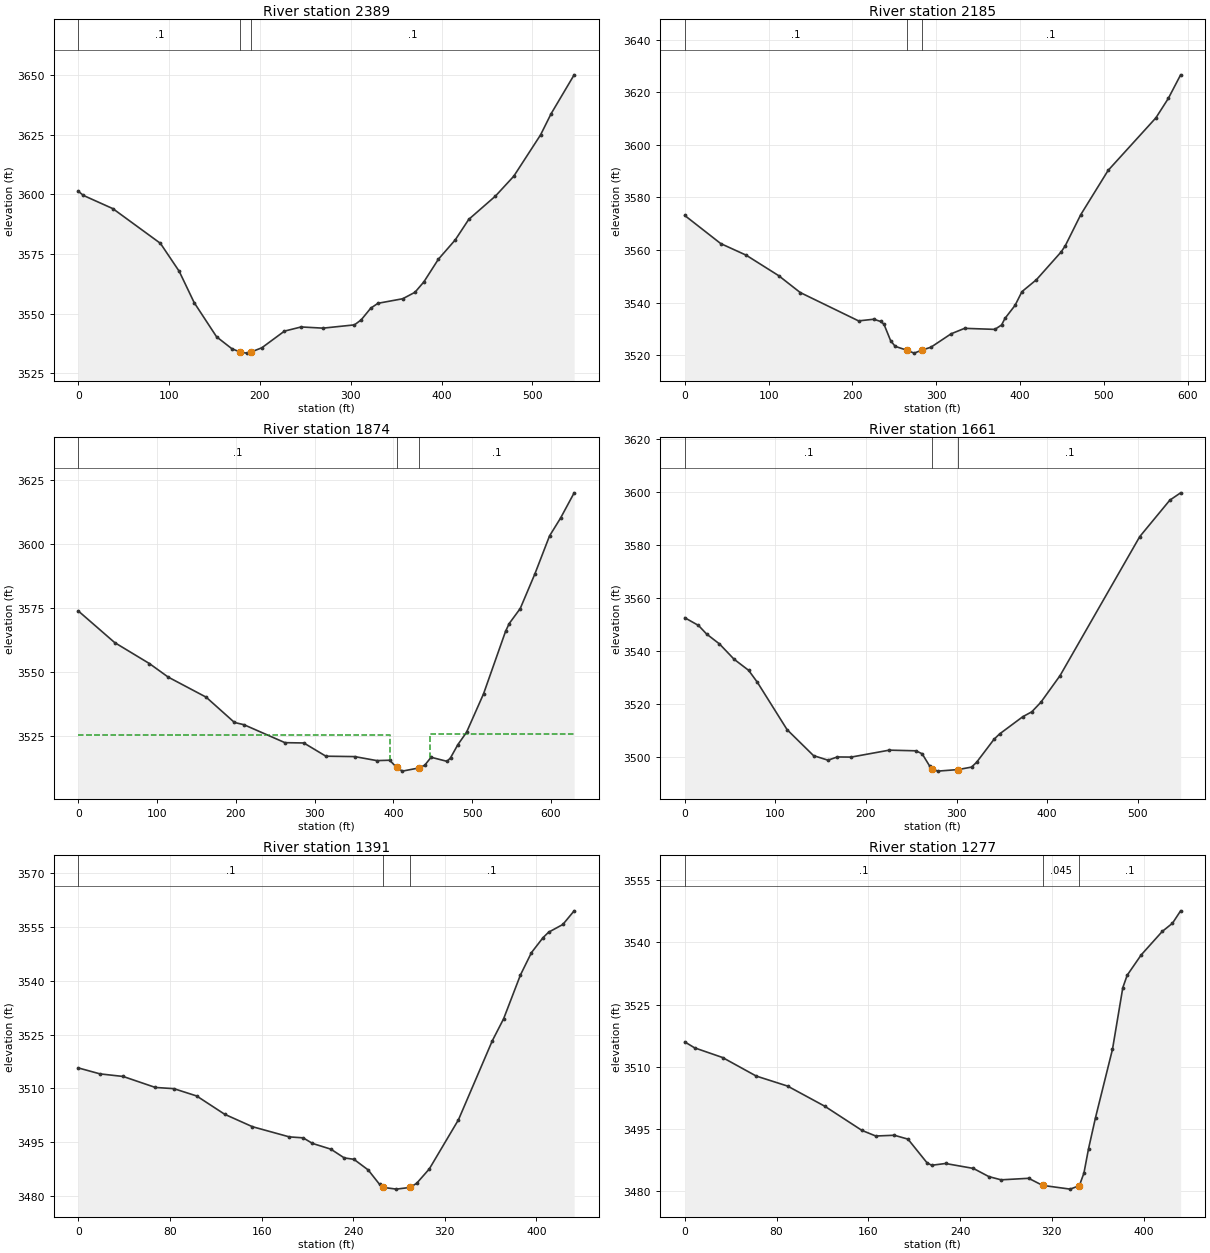
Type RM Length L Ch R = 1 ,2389    ,221,204.1,180.4
XS GIS Cut Line= 5
2198930.01439819497871.7103272042198947.73448574497981.437411753
2198977.68334583498091.7208547992199005.97589019498174.238816801
2199143.09041173498363.106932514
#Sta/Elev= 30
       0 3601.34     5.5  3599.6      38 3594.05    90.4 3579.49   111.1 3567.76
   127.6 3554.62   152.3 3540.27   168.9 3535.35   178.4 3533.83   185.5 3533.44
   189.8 3533.85   202.1 3535.68     227 3542.67   245.4 3544.42   269.5 3543.92
   304.1 3545.29   311.5 3547.38   322.1 3552.31     330 3554.34   357.3 3556.25
   370.8 3558.97   380.6 3563.34   396.5  3572.8   415.2 3580.97     430 3589.54
   459.4 3599.31   479.6 3607.65   509.1 3624.98   520.7 3633.85   546.1 3650.17
#Mann= 3 ,0,0
       0      .1       0   178.4    .045       0   189.8      .1       0
Bank Sta=178.4,189.8
XS Rating Curve= 0 ,0
Exp/Cntr=0.3,0.1

Type RM Length L Ch R = 1 ,2185    ,293.5,311.1,348.1
XS GIS Cut Line= 4
2198709.08716006498041.3017755582198786.09084472498233.810987203
2198980.43347743498219.1436186972199090.43874123498373.150988013
#Sta/Elev= 30
       0 3573.15    42.9 3562.47    73.1 3558.09   111.9 3550.31   137.7 3543.88
   207.3 3533.11   225.5 3533.74   233.5 3532.89   237.5 3531.91   245.5 3525.63
   250.9 3523.45   265.3 3521.92   273.6 3520.86   282.7 3521.98   293.7 3523.12
   317.7  3528.2   333.8 3530.28   369.9 3529.88   377.9 3531.56   381.9 3534.03
     394 3539.01   402.2 3544.22   419.5 3548.76     449 3559.32   453.9 3561.66
   472.3 3573.43     505 3590.28     562 3610.25   576.8 3617.62   591.5 3626.59
#Mann= 3 ,0,0
       0      .1       0   265.3    .045       0   282.7      .1       0
Bank Sta=265.3,282.7
XS Rating Curve= 0 ,0
Exp/Cntr(USF)=0,0
Exp/Cntr=0.3,0.1

Type RM Length L Ch R = 1 ,1874    ,220.4,213.2,200.1
XS GIS Cut Line= 4
2198687.54660379498047.0507551332198674.48974122498358.693672547
2198699.02516428498514.9455772732198780.81986545498652.041228052
#Sta/Elev= 30
       0 3573.85    46.2 3561.52    90.2 3553.36   114.2 3548.06   162.3 3540.25
   198.3 3530.37   210.3 3529.51   262.4  3522.5   286.4 3522.38   314.4 3517.22
   350.9 3517.07   379.2  3515.5   395.4 3515.65   404.1 3512.89   411.6  3511.4
     433 3512.67     440 3513.72     448 3516.81   468.3 3515.21   472.7  3516.6
     482 3521.73     493 3526.54   514.6 3541.53   542.6 3565.93   547.2 3568.95
   561.2  3574.8   579.8  3588.3   598.4 3603.11   612.4 3610.07   629.7 3619.93
#Mann= 3 ,-1,0
       0      .1       0   404.1    .045       0     433      .1       0
#XS Ineff= 2 , 0
           395.6 3525.66  447.06         3525.84
Permanent Ineff=
       F       F
Bank Sta=404.1,433
XS Rating Curve= 0 ,0
Exp/Cntr(USF)=0,0
Exp/Cntr=0.3,0.1

Type RM Length L Ch R = 1 ,1661    ,274.1,269.5,263.3
XS GIS Cut Line= 4
2198351.17132976498290.2391125942198412.47441304498426.046003918
2198569.22975548498623.211265744 2198689.9442728498706.055378187
#Sta/Elev= 30
       0  3552.5    15.1  3549.6    24.1 3546.35    38.3 3542.61    54.4 3536.84
    70.5 3532.64    80.2 3528.09   112.9 3510.26   142.1 3500.45   158.1 3498.73
   168.3 3499.95   183.7  3499.9   225.7 3502.52   255.2 3502.27     262 3501.14
   270.5 3496.39   273.4 3495.55   279.1  3494.6   301.9 3495.19   316.5 3496.12
   322.1 3497.94   341.3 3506.61   347.4 3508.62   373.1 3515.15     383 3516.99
     393 3520.58   414.2 3530.65   502.2 3583.14   535.4  3596.9   547.3 3599.66
#Mann= 3 ,-1,0
       0      .1       0   273.4    .045       0   301.9      .1       0
Bank Sta=273.4,301.9
XS Rating Curve= 0 ,0
Exp/Cntr=0.3,0.1

Type RM Length L Ch R = 1 ,1391    ,86.5,114.2,130.7
XS GIS Cut Line= 3
2198279.06687821498482.3890335132198309.39082578498725.284237077
 2198462.2724093 498834.93625976
#Sta/Elev= 30
       0 3515.68    18.9 3514.02    39.1  3513.3    67.3 3510.23    83.4  3509.9
   103.3 3507.86   127.8 3502.75     152 3499.29   184.2 3496.45   196.3 3496.18
   204.4 3494.63   220.5 3493.02   232.2 3490.58   240.6  3490.2   253.1 3487.22
     263 3483.21  266.27 3482.36   277.7 3481.88   289.7 3482.36   295.4 3483.51
   306.4  3487.5   331.9 3501.23   361.4 3523.23   371.3 3529.38     386  3541.6
   395.6 3547.83   405.7    3552   410.6 3553.53     423 3555.68   432.9 3559.49
#Mann= 3 ,-1,0
       0      .1       0  266.27    .045       0   289.7      .1       0
Bank Sta=266.27,289.7
XS Rating Curve= 0 ,0
Exp/Cntr=0.3,0.1

Type RM Length L Ch R = 1 ,1277    ,294.6,295.7,292.1
XS GIS Cut Line= 4
2198237.27464876 498500.706865372198278.05098497498756.578375084
2198269.89571773498854.4415819862198298.43915308498923.761353542
#Sta/Elev= 30
       0 3515.95     8.6 3514.51    32.9 3512.18    62.3 3507.69    89.6 3505.27
     122  3500.4   154.4 3494.55   166.5 3493.19   182.7 3493.37   194.6 3492.43
   211.1 3486.74   215.2 3486.11   227.3 3486.54   251.6 3485.35   265.1 3483.37
   275.8 3482.59   299.8 3482.96   311.9 3481.25     336 3480.34     344 3481.18
     348 3484.23     352  3490.1   358.1 3497.65   372.9 3514.18   381.9 3529.08
   385.7 3532.08   397.9 3536.99   416.3 3542.68   425.2 3544.66   432.3 3547.66
#Mann= 3 ,-1,0
       0      .1       0   311.9    .045       0     344      .1       0
Bank Sta=311.9,344
XS Rating Curve= 0 ,0
Exp/Cntr(USF)=0,0
Exp/Cntr=0.3,0.1

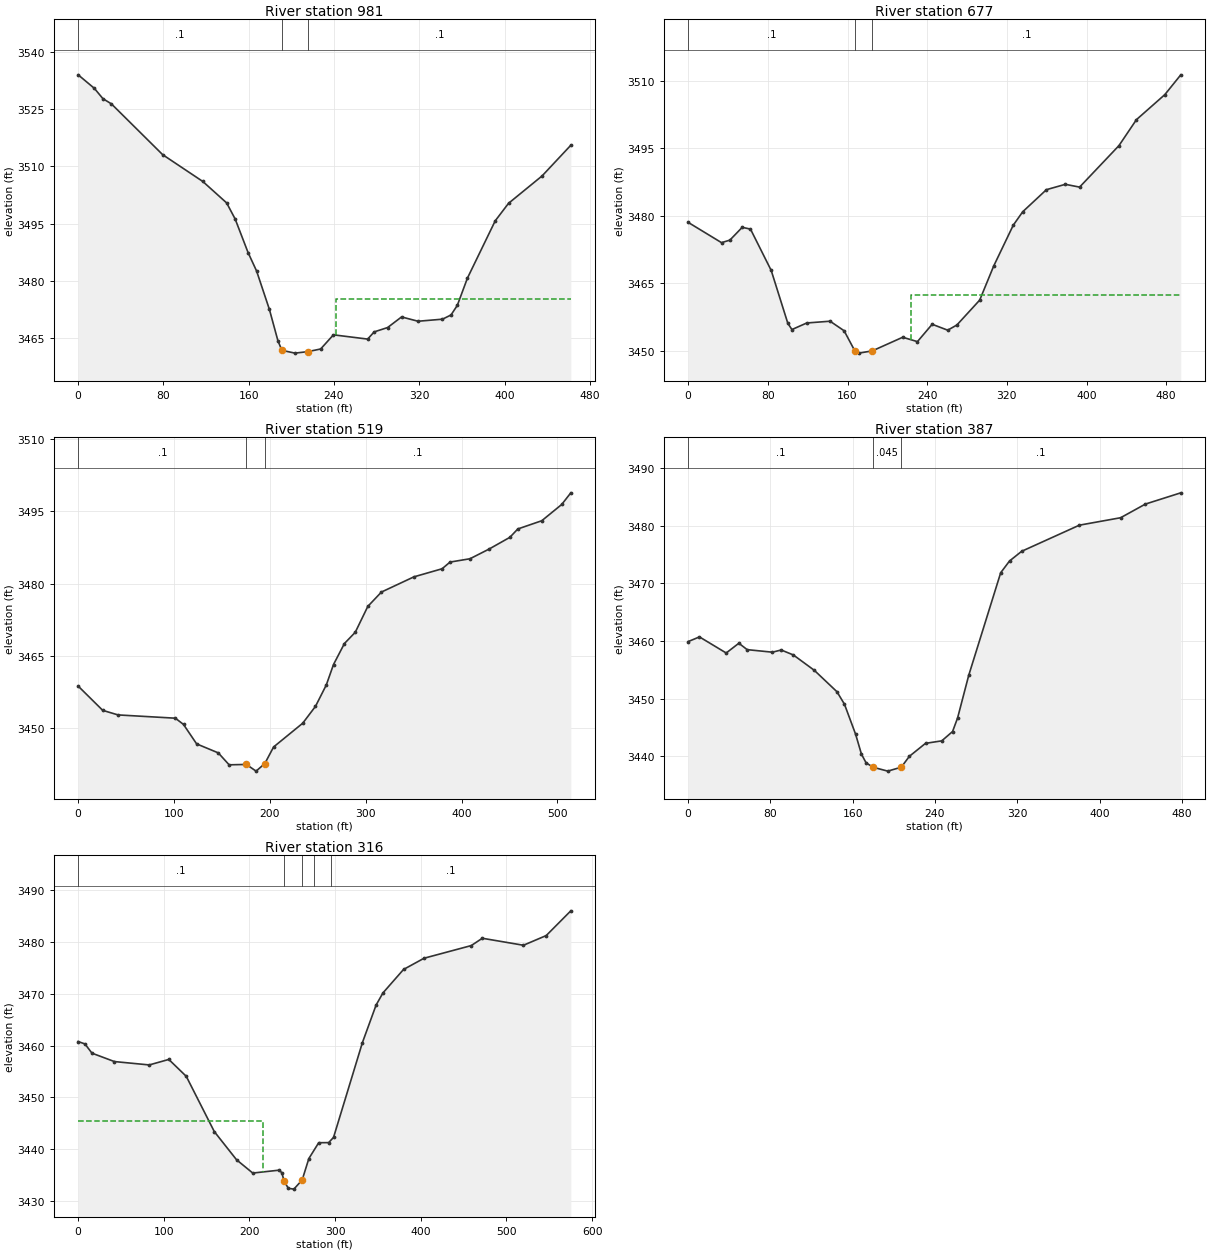
Type RM Length L Ch R = 1 ,981     ,310.9,304.1,291.5
XS GIS Cut Line= 3
2198024.67617017498482.0212099162198037.04968355498725.016993852
2198150.38088478498912.265556923
#Sta/Elev= 30
       0 3534.09    15.2 3530.53    23.2 3527.83    31.2 3526.45    79.3  3513.1
   116.9 3506.07   139.3 3500.43   147.3 3496.19   159.4 3487.38   167.4 3482.53
   179.4 3472.45   187.4 3464.21191.11413461.683   203.4 3460.95215.64423461.346
   227.5 3462.04   239.5 3465.76   271.6 3464.64   277.7 3466.53   290.3 3467.67
   303.4 3470.46   318.9 3469.33   341.8 3469.87   349.8 3470.98   355.7 3473.49
   365.2 3480.66   391.3 3495.73   403.8 3500.33   435.2 3507.51   462.2 3515.58
#Mann= 3 ,-1,0
       0      .1       0191.1141    .045       0215.6442      .1       0
#XS Ineff= 2 , 0
                          241.93         3475.22
Permanent Ineff=
       F       F
Bank Sta=191.1141,215.6442
XS Rating Curve= 0 ,0
Exp/Cntr(USF)=0,0
Exp/Cntr=0.3,0.1

Type RM Length L Ch R = 1 ,677     ,159.6,157.9,155.3
XS GIS Cut Line= 4
2197745.35799872498660.9183934732197779.51606638498781.250290202
2197887.76972691498889.7864797082198069.66061086499006.776901244
#Sta/Elev= 30
       0 3478.54    33.5 3474.04    41.9  3474.6    54.3 3477.44    62.6 3477.04
    83.4 3467.87   100.1 3456.13   104.2 3454.76   119.1 3456.22   142.5 3456.61
   156.6 3454.49  167.41    3450   171.3 3449.53   184.9 3450.03   215.4 3453.05
   230.2 3452.08     245 3455.93   260.6 3454.62   269.8 3455.77   292.7 3461.29
   306.8 3468.87   326.4 3477.91   335.9 3480.89   359.7 3485.79   378.7 3486.98
     393 3486.36   432.5 3495.56   450.1 3501.33   478.6 3506.88   494.6 3511.27
#Mann= 3 ,0,0
       0      .1       0  167.41    .045       0   184.9      .1       0
#XS Ineff= 2 , 0
                          223.58         3462.45
Permanent Ineff=
       F       F
Bank Sta=167.41,184.9
XS Rating Curve= 0 ,0
Exp/Cntr=0.3,0.1

Type RM Length L Ch R = 1 ,519     ,133.2,132.5,130.6
XS GIS Cut Line= 4
2197607.56315931498803.5954304872197611.39094038498892.734423946
2197804.29452646499087.2322545412197949.37077715499128.682611881
#Sta/Elev= 30
       0 3458.71    25.6 3453.67    41.6 3452.72   101.4 3452.04   109.9 3450.74
   123.6  3446.7   146.2 3444.83   157.5 3442.35   175.5 3442.43   185.6 3441.04
   194.7  3442.6   203.9 3446.06   234.3    3451   247.6  3454.5   258.9 3458.95
   266.4 3463.19   277.8 3467.56   289.1 3469.89   302.2 3475.27   316.4 3478.25
   350.3 3481.41   379.7 3483.09     388 3484.48   408.8 3485.17   428.5 3487.16
   450.4 3489.62   458.7 3491.36   483.7 3493.07   504.5 3496.45     514 3498.87
#Mann= 3 ,-1,0
       0      .1       0   175.5    .045       0   194.7      .1       0
Bank Sta=175.5,194.7
XS Rating Curve= 0 ,0
Exp/Cntr(USF)=0,0
Exp/Cntr=0.3,0.1

Type RM Length L Ch R = 1 ,387     ,72,70.7,67.7
XS GIS Cut Line= 4
2197578.33356993498884.8797070322197550.90554963499022.019808535
2197675.84250651499128.3614974132197850.52180529499139.867319488
#Sta/Elev= 30
       0 3459.91      11 3460.72      37 3457.93    49.3 3459.62    57.4 3458.51
    81.9 3458.07    90.5 3458.45   102.3 3457.59   122.7 3454.92   144.7 3451.21
     152 3449.04   162.9  3443.8   168.5 3440.39     173 3438.88   179.9 3438.11
   194.1 3437.44  207.263438.126   215.1 3440.01   230.8 3442.26   246.6 3442.69
   257.1 3444.31     262 3446.67   272.8 3454.05   303.9 3471.85   312.5 3473.89
   324.3 3475.57   380.4  3480.1   420.5 3481.39   444.6 3483.76     479 3485.71
#Mann= 3 ,-1,0
       0      .1       0   179.9    .045       0  207.26      .1       0
Bank Sta=179.9,207.26
XS Rating Curve= 0 ,0
Exp/Cntr(USF)=0,0
Exp/Cntr=0.3,0.1

Type RM Length L Ch R = 1 ,316     ,48.7,48.4,48.7
XS GIS Cut Line= 4
2197558.30766424498889.4464306052197517.63051548 499090.50776586
2197612.93126399499155.5912038622197867.45399474499160.240020862
#Sta/Elev= 30
       0 3460.78     7.9 3460.32    16.1 3458.54    42.3 3456.92      83 3456.27
   105.8 3457.33   126.2 3454.07   158.9 3443.42   184.9 3437.98   203.8 3435.42
   234.8 3435.98   237.7 3435.48   240.5 3433.86   245.3 3432.48   251.8 3432.32
   261.5 3434.09   269.3 3438.22   280.8 3441.27   292.4 3441.29   298.1 3442.29
   331.8 3460.57   347.8 3467.82   355.8 3470.16   379.8 3474.68   403.8 3476.85
   458.9 3479.29   471.8  3480.7   519.8 3479.35   546.4 3481.22   575.1 3485.99
#Mann= 5 ,-1,0
       0      .1       0   240.5    .045       0   261.5      .1       0
  275.13     .06       0  295.13      .1       0
#XS Ineff= 2 , 0
             216 3445.42
Permanent Ineff=
       F       F
Bank Sta=240.5,261.5
XS Rating Curve= 0 ,0
Exp/Cntr(USF)=0,0
Exp/Cntr=0.3,0.1