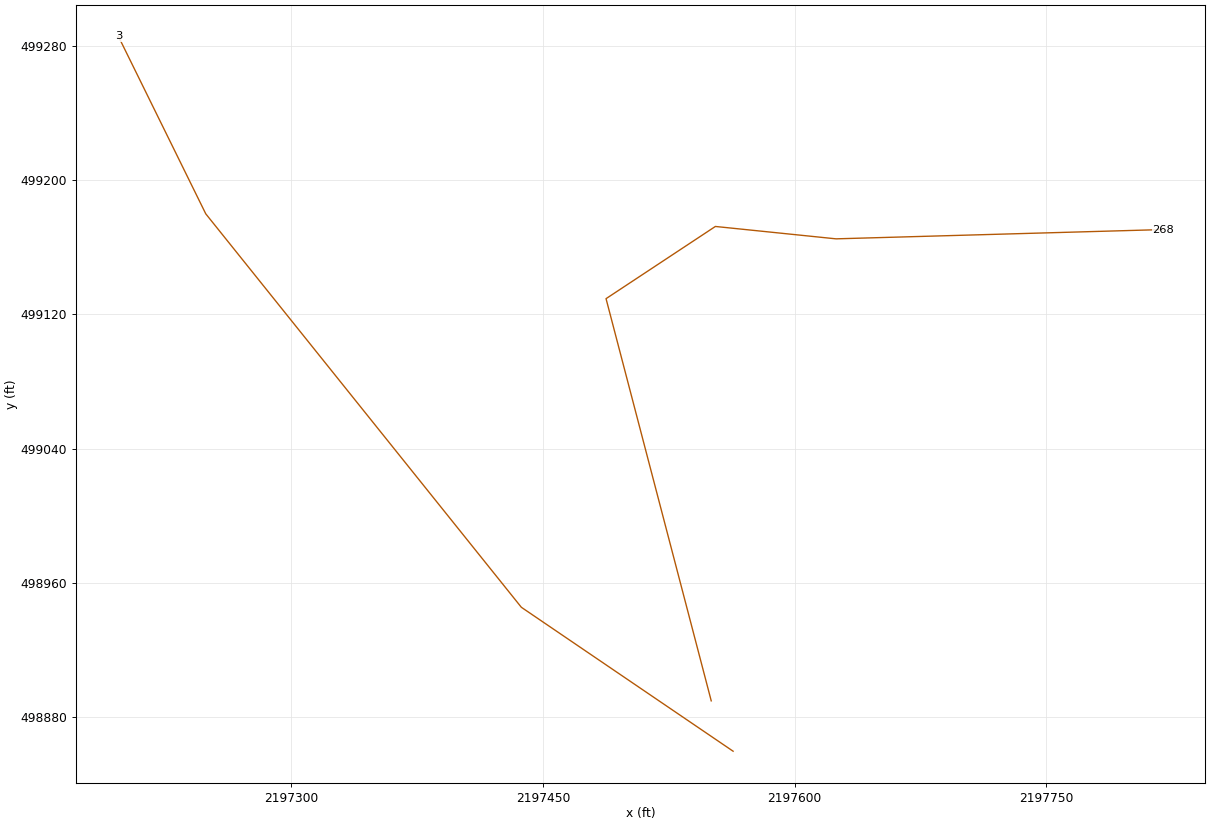
HEC-RAS study RFKTEACK.prj: RFKTEACK

--- RFKTEACK.g01 (geometry) --- (continued)

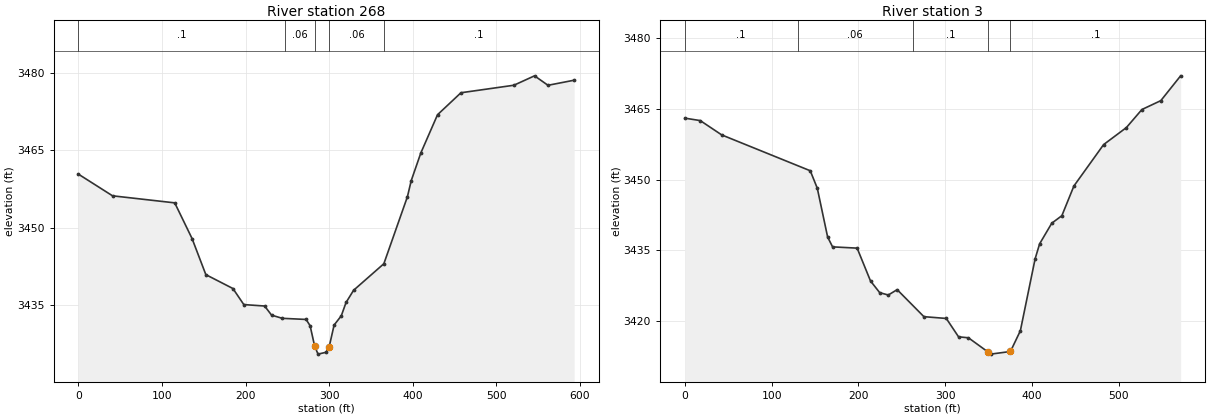
Type RM Length L Ch R = 1 ,268     ,228.8,264.2,299.9
XS GIS Cut Line= 5
2197550.33224334498889.6103334712197487.64200349 499129.30830937
2197552.79068412499172.3310229932197624.70007689499164.955700657
2197819.53150858499170.487192409
#Sta/Elev= 30
       0  3460.4    40.9 3456.18   115.3 3454.81     136 3447.88   152.5 3440.86
   184.9 3438.16   197.9 3435.04   222.8 3434.76   231.1 3432.99   243.9 3432.37
   272.4 3432.15   277.2 3430.93   282.7 3426.91   286.7 3425.41   296.3 3425.77
     300 3426.83   305.9 3431.06   314.5 3432.86   320.2 3435.45   329.2 3437.82
   365.4 3442.98   393.6 3456.01   398.1 3459.11   409.6  3464.5   429.6 3471.94
   457.6 3476.21   520.9 3477.67   545.6  3479.5   561.7 3477.66     593 3478.65
#Mann= 5 ,-1,0
       0      .1       0  247.76     .06       0   282.7    .045       0
     300     .06       0  365.83      .1       0
Bank Sta=282.7,300
XS Rating Curve= 0 ,0
Exp/Cntr(USF)=0,0
Exp/Cntr=0.3,0.1

Type RM Length L Ch R = 1 ,3       ,474.4,,474.4
XS GIS Cut Line= 4
2197563.35625343498859.6124707012197437.15218408498945.397889667
2197249.09159232499179.8644271062197197.01873767499285.638757529
#Sta/Elev= 30
       0 3463.05    17.8 3462.53    42.5 3459.49   144.5 3451.87   152.6 3448.16
   164.5  3437.8   170.2  3435.7   198.5 3435.43   213.9 3428.46   224.5 3425.97
   234.4 3425.47   244.6 3426.61   275.4 3420.87   301.2 3420.49   315.3 3416.59
   326.7 3416.38   349.5 3413.33   352.3 3412.91   375.1 3413.47   386.5 3417.87
   403.5 3433.16   408.7 3436.35   422.7 3440.73   434.3 3442.32   448.2 3448.64
   482.4 3457.43   508.6 3461.04   526.5 3464.88   548.3 3466.77   571.1 3472.04
#Mann= 5 ,-1,0
       0      .1       0     130     .06       0   262.6      .1       0
   349.5    .045       0   375.1      .1       0
Bank Sta=349.5,375.1
XS Rating Curve= 0 ,0
Exp/Cntr(USF)=0,0
Exp/Cntr=0.3,0.1
LCMann Table=0

Chan Stop Cuts=-1
Use User Specified Reach Order=0
Composite Channel Slope=5